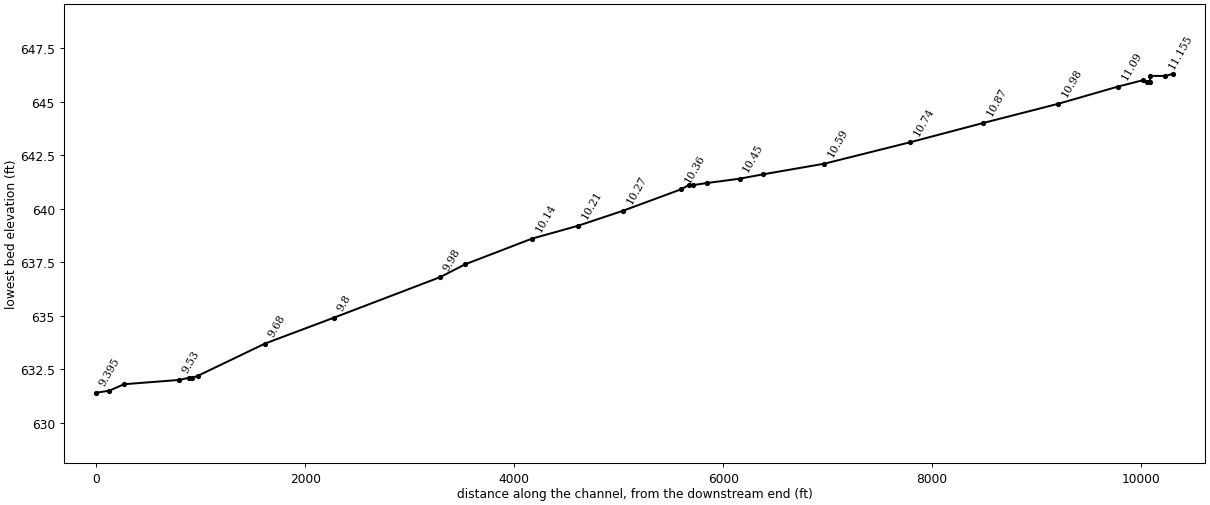
--- B30_143_144.prj (project) ---

Proj Title=Pike River
Current Plan=p10
Current HD=h01
Default Exp/Contr=0.3,0.1
English Units
Geom File=g08
Geom File=g01
Geom File=g05
Geom File=g02
Geom File=g10
Flow File=f08
Plan File=p08
Plan File=p02
Plan File=p01
Plan File=p03
Plan File=p10
HD File=h01
Y Axis Title=Elevation
X Axis Title(PF)=Main Channel Distance
X Axis Title(XS)=Station
BEGIN DESCRIPTION:
 PIKE RIVER WATERSHED STUDY - 1994 AMENDMENT
  (REFINEMENT OF RECOMMENDED FLOOD CONTROL PLAN RESULTING
   FROM ENVIRONMENTAL IMPACT STATEMENT REVIEW PROCESS)
 YEAR 2010 PLANNED LAND USE, EXISTING CHANNEL CONDITIONS
  DISCHARGES WERE DEVELOPED USING U.S. EPA HSPF MODEL
 PIKE RIVER MAIN STEM PART 4                 100-YEAR R.I. EVENT
      FILE: PR4PLEX                   9:40 A.M.      8/22/94
WAE 2017-09-15: PROPOSED PEDESTRAIN BRIDGE AT SECTION 11.14
WisDOT update - September 2018.  Proposed CTH KR bridges at 11.1525.  Also included some updates to geometry and reach lengths between Proposed KR bridges and the downstream pedestrian bridge.  WisDOT SGN
END DESCRIPTION:
DSS Export Rating Curves= 0
DSS Export Rating Curve Sorted= 0
DSS Export Volume Flow Curves= 0
DXF Filename=pikeriver.
DXF OffsetX= 0
DXF OffsetY= 0
DXF ScaleX= 1
DXF ScaleY= 10

--- B30_143_144.p10 (plan) ---

Plan Title=Proposed 233' 5span slab
Program Version=5.03
Short Identifier=Prop233' 5sp slab
Geom File=g10
Flow File=f08
Subcritical Flow
K Sum by GR= 0
Std Step Tol= 0.01
Critical Tol= 0.01
Num of Std Step Trials= 20
Max Error Tol= 0.3
Flow Tol Ratio= 0.001
Split Flow NTrial= 30
Split Flow Tol= 0.02
Split Flow Ratio= 0.02
Log Output Level= 0
Friction Slope Method= 1
Unsteady Friction Slope Method= 2
Unsteady Bridges Friction Slope Method= 1
Parabolic Critical Depth
Global Vel Dist= 0 , 0 , 0
Global Log Level= 0
CheckData=True
Encroach Param=-1 ,0,0, 0
Computation Interval=1MIN
Output Interval=1HOUR
Instantaneous Interval=1HOUR
Mapping Interval=1HOUR
Run HTab= 0
Run UNet= 0
Run Sediment= 0
Run PostProcess= 0
Run WQNet= 0
Run RASMapper= 0
UNET Theta= 1
UNET Theta Warmup= 1
UNET ZTol= 0.02
UNET ZSATol= 0.02
UNET MxIter= 20
UNET Max Iter WO Improvement= 0
UNET MaxInSteps= 0
UNET DtIC= 0
UNET DtMin= 0
UNET MaxCRTS= 20
UNET WFStab= 2
UNET SFStab= 1
UNET WFX= 1
UNET SFX= 1
UNET DSS MLevel= 4
UNET Pardiso=0
UNET DZMax Abort= 100
UNET Use Existing IB Tables=-1
UNET Froude Reduction=False
UNET Froude Limit= 0.8
UNET Froude Power= 4
UNET Time Slicing=0,0, 5
UNET D1 Cores= 0
UNET D2 Coriolis=0
UNET D2 Cores= 0
UNET D2 Theta= 1
UNET D2 Theta Warmup= 1
UNET D2 Z Tol= 0.01
UNET D2 Volume Tol= 0.01
UNET D2 Max Iterations= 20
UNET D2 Equation= 0
UNET D2 RampUpFraction=0.1
UNET D2 TimeSlices= 1
UNET D2 BCVolumeCheck=0
UNET D1D2 MaxIter= 0
UNET D1D2 ZTol=0.01
UNET D1D2 QTol=0.1
UNET D1D2 MinQTol=1
Write IC File= 0
Write IC File at Fixed DateTime=0
Write IC File at Sim End=0
Echo Input=False
Echo Parameters=False
Echo Output=False
Write Detailed= 0
HDF Write Warmup=0
HDF Write Time Slices=0
HDF Flush=0
HDF Face Node Velocities=0
HDF Compression= 1
HDF Chunk Size= 1
HDF Spatial Parts= 1
HDF Use Max Rows=0
HDF Fixed Rows= 1
Calibration Method= 0
Calibration Iterations= 20
Calibration Max Change=0.05
Calibration Tolerance=0.2
Calibration Maximum=1.5
Calibration Minimum=0.5
Calibration Optimization Method= 1
WQ AD Non Conservative
WQ ULTIMATE=-1
WQ Max Comp Step=1HOUR
WQ Output Interval=15MIN
WQ Output Selected Increments= 0
WQ Output face flow=0
WQ Output face velocity=0
WQ Output face area=0
WQ Output face dispersion=0
WQ Output cell volume=0
WQ Output cell surface area=0
WQ Output cell continuity=0
WQ Output cumulative cell continuity=0
WQ Output face conc=0
WQ Output face dconc_dx=0
WQ Output face courant=0
WQ Output face peclet=0
WQ Output face adv mass=0
WQ Output face disp mass=0
WQ Output cell mass=0
WQ Output cell source sink temp=0
WQ Output nsm pathways=0
WQ Output nsm derived pathways=0
WQ Output MaxMinRange=-1
WQ Daily Max Min Mean=-1
WQ Daily Range=0
WQ Daily Time=0
WQ Create Restart=0
WQ Fixed Restart=0
WQ System Summary=0
WQ Write To DSS=0
WQ Use Fixed Temperature=0
Sorting and Armoring Iterations= 10
XS Update Threshold= 0.02
Bed Roughness Predictor= 0
Hydraulics Update Threshold= 0.02
Energy Slope Method= 1
Volume Change Method= 1
Sediment Retention Method= 0
XS Weighting Method= 0
Number of US Weighted Cross Sections= 1
Number of DS Weighted Cross Sections= 1
Upstream XS Weight=0
Main XS Weight=1
Downstream XS Weight=0
Number of DS XS's Weighted with US Boundary= 1
Upstream Boundary Weight= 1
Weight of XSs Associated with US Boundary= 0
Number of US XS's Weighted with DS Boundary= 1
Downstream Boundary Weight= 0.5
Weight of XSs Associated with DS Boundary= 0.5
Percentile Method= 0
Sediment Output Level= 4
Mass or Volume Output= 0
Output Increment Type= 1
Profile and TS Output Increment= 1
XS Output Flag= 0
XS Output Increment= 10
Write Gradation File= 0
Read Gradation Hotstart= 0
Write HDF5 File= 1
Write DSS Sediment File= 0
SV Curve= 0
Specific Gage Flag= 0

--- B30_143_144.p01 (plan) ---

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Plan Title=Proposed Ped Bridge - Corrected
Program Version=4.10
Short Identifier=Prop
Geom File=g05
Flow File=f08
Computation Interval=1HOUR
UNET ZSATol= 0.05
UNET Convert EG Bridges= 0
UNET Froude Limit= 1
UNET Froude Power= 10
UNET Junction Losses=0
WQ Output cell source sink nsm=0
Volume Change Method= 0
Upstream XS Weight=0.25
Main XS Weight=0.5
Downstream XS Weight=0.25
Profile and TS Output Increment= 10
Disregard all LS=0
Disregard all Conn=0
Disregard all Breaches=0
Disregard all Pumps=0

--- B30_143_144.p02 (plan) ---

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Plan Title=Existing Condition - Corrected Effective
Program Version=4.10
Short Identifier=ExCorrected
Geom File=g01
Flow File=f08
Computation Interval=1HOUR
UNET ZSATol= 0.05
UNET Convert EG Bridges= 0
UNET Froude Limit= 1
UNET Froude Power= 10
UNET Junction Losses=0
WQ Output cell source sink nsm=0
Volume Change Method= 0
Upstream XS Weight=0.25
Main XS Weight=0.5
Downstream XS Weight=0.25
Profile and TS Output Increment= 10
Disregard all LS=0
Disregard all Conn=0
Disregard all Breaches=0
Disregard all Pumps=0

--- B30_143_144.p03 (plan) ---

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Plan Title=WisDOT Corrected geometry-8/2018
Short Identifier=WisDOT Corrected existing
Geom File=g02
Flow File=f08

--- B30_143_144.p08 (plan) ---

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Plan Title=Existing Condition
Program Version=4.10
Short Identifier=Exist
Geom File=g08
Flow File=f08
Computation Interval=1HOUR
UNET ZSATol= 0.05
UNET Convert EG Bridges= 0
UNET Froude Limit= 1
UNET Froude Power= 10
UNET Junction Losses=0
WQ Output cell source sink nsm=0
Volume Change Method= 0
Upstream XS Weight=0.25
Main XS Weight=0.5
Downstream XS Weight=0.25
Profile and TS Output Increment= 10
Disregard all LS=0
Disregard all Conn=0
Disregard all Breaches=0
Disregard all Pumps=0

--- B30_143_144.f08 (steady flow) ---

Flow Title=Flow
Program Version=5.03
Number of Profiles= 4
Profile Names=1% Flow,2% Flow,10% Flow,Q2
River Rch & RM=RIVER-1,Reach-1         ,11.19
    2840    2430    1420    1130
River Rch & RM=RIVER-1,Reach-1         ,10.49
    2840    2420    1400    1130
River Rch & RM=RIVER-1,Reach-1         ,9.56
    4020    3390    2150    1130
Boundary for River Rch & Prof#=RIVER-1,Reach-1         , 1
Up Type= 0
Dn Type= 1
Dn Known WS=640.73
Boundary for River Rch & Prof#=RIVER-1,Reach-1         , 2
Up Type= 0
Dn Type= 1
Dn Known WS=640.28
Boundary for River Rch & Prof#=RIVER-1,Reach-1         , 3
Up Type= 0
Dn Type= 1
Dn Known WS=639.16
DSS Import GetInterval= 0
DSS Import GetPeak= 0
DSS Import FillOption= 0

--- B30_143_144.g10 (geometry) ---

Geom Title=Proposed 233' 5 span slab
Program Version=5.03

River Reach=RIVER-1         ,Reach-1
Reach XY= 2
             0.5            0.95             0.5            0.05

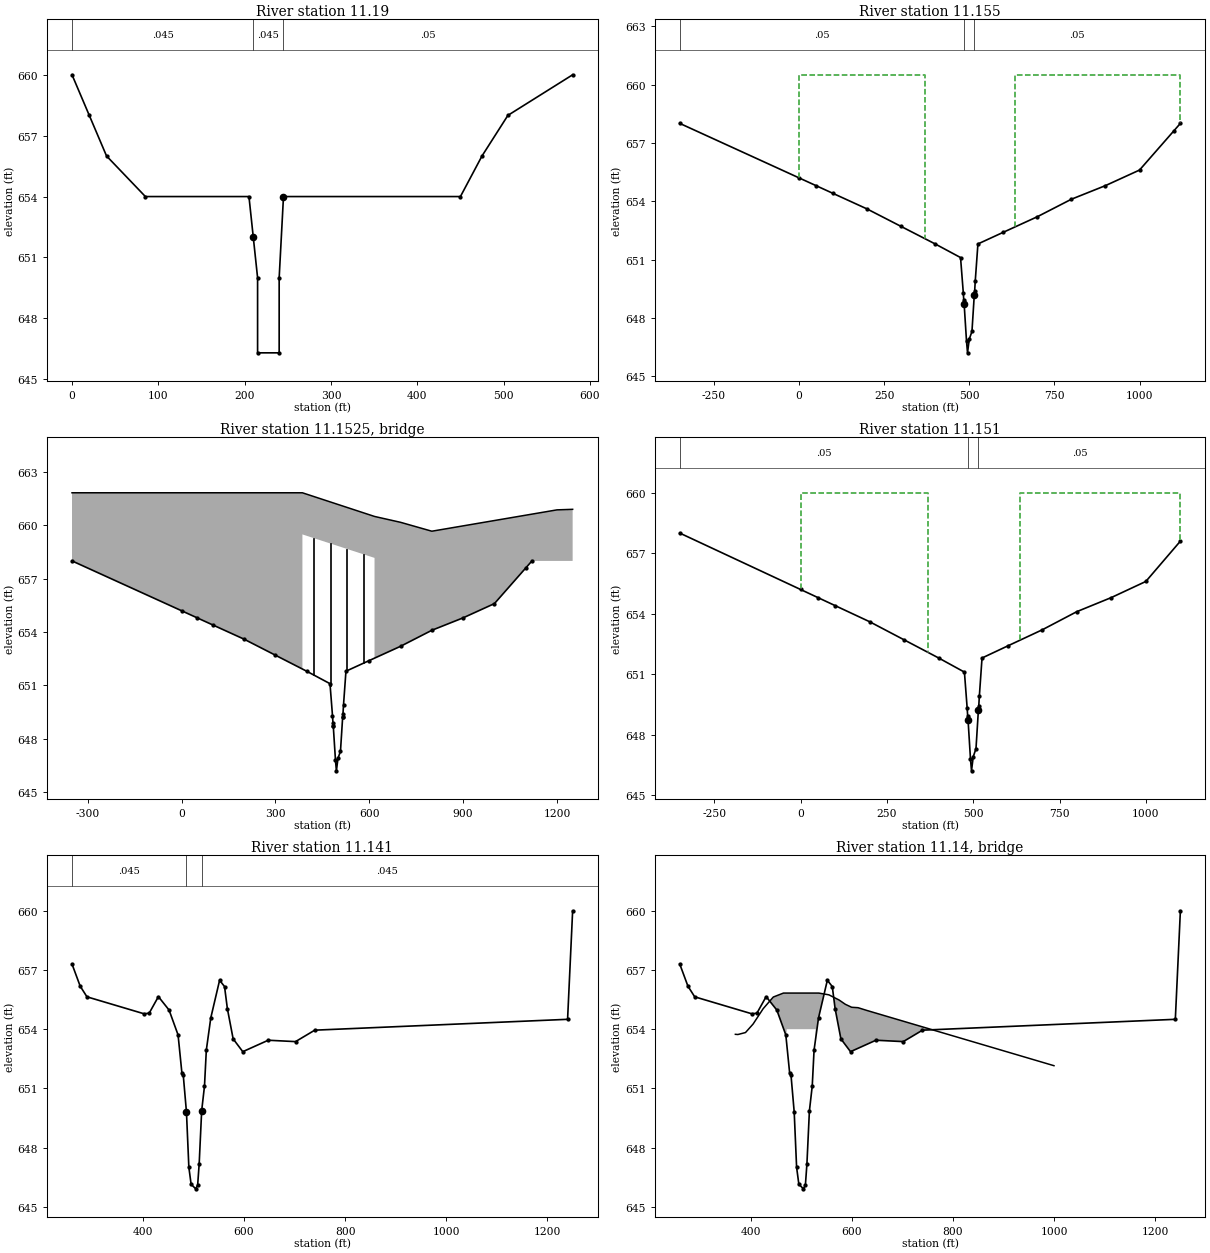
Type RM Length L Ch R = 1 ,11.19   ,74,74,84
#Sta/Elev= 15
       0     660      20     658      40     656      85     654     205     654
     210     652     215     650     215   646.3     240   646.3     240     650
     245     654     450     654     475     656     505     658     580     660
#Mann= 3 , 0 , 0
       0    .045       0     210    .045       0     245     .05       0
Bank Sta=210,245
XS Rating Curve= 0 ,0
Sediment Elevation=0
Exp/Cntr=0.3,0.1

Type RM Length L Ch R = 1 ,11.155  ,146,146,146
BEGIN DESCRIPTION:
This is a REPEATED section.
END DESCRIPTION:
#Sta/Elev= 28
    -350     658       0   655.2      50   654.8     100   654.4     200   653.6
     300   652.7     400   651.8   474.5   651.1   482.5   649.3     484   648.9
     485   648.7   485.1   648.7     492   646.8     495   646.2     500   646.9
     508   647.3   514.9   649.2     515   649.2     516   649.4   517.7   649.9
   525.5   651.8     600   652.4     700   653.2     800   654.1     900   654.8
    1000   655.6    1100   657.6    1120     658
#Mann= 3 , 0 , 0
    -350     .05       0     485    .035       0     515     .05       0
#XS Ineff= 2 , 0
       0     370   660.5     635       0   660.5
Permanent Ineff=
       F       F
Bank Sta=485,515
XS Rating Curve= 0 ,0
Sediment Elevation=0
Exp/Cntr=0.5,0.3

Type RM Length L Ch R = 3 ,11.1525 ,,,
BEGIN DESCRIPTION:
Bridge #4 - Culvert at CTH KR - WisDOT update to reflect 3 cells in the culvert
WisDOT SGN - August 2018
END DESCRIPTION:
Bridge Culvert--1,0,-1,-1, 0
Deck Dist Width WeirC Skew NumUp NumDn MinLoCord MaxHiCord MaxSubmerge Is_Ogee
0.5,145,2.5,0, 14, 14, 656.1, , 0.98, 0, 0,0,,
    -350       0      50     100     200     300  386.35  386.35  616.85  616.85
     700     800    1200    1250
  661.83  661.83  661.83  661.83  661.83  661.83  661.83  661.83   660.5   660.5
  660.17  659.67  660.87   660.9
                                                          659.49  658.17
                                
    -350       0      50     100     200     300  386.35  386.35  616.85  616.85
     700     800    1200    1250
  661.83  661.83  661.83  661.83  661.83  661.83  661.83  661.83   660.5   660.5
  660.17  659.67  660.87   660.9
                                                          659.49  658.17
                                
Pier Skew, UpSta & Num, DnSta & Num=  ,422.1, 2 ,422.1, 2 , 0 , 0 , 0 ,,
     2.5     2.5
     640   659.5
     2.5     2.5
     640   659.5
Pier Skew, UpSta & Num, DnSta & Num=  ,475.1, 2 ,475.1, 2 , 0 , 0 , 0 ,,
     2.5     2.5
     640     659
     2.5     2.5
     640     659
Pier Skew, UpSta & Num, DnSta & Num=  ,528.1, 2 ,528.1, 2 , 0 , 0 , 0 ,,
     2.5     2.5
     640     659
     2.5     2.5
     640     659
Pier Skew, UpSta & Num, DnSta & Num=  ,581.1, 2 ,581.1, 2 , 0 , 0 , 0 ,,
     2.5     2.5
     640     659
     2.5     2.5
     640     659
Abutment Skew #Up #Dn= , 3 , 3
  386.35  388.85  395.97
  656.99  656.99     652
  386.35  388.85  395.97
  656.99  656.99     652
Abutment Skew #Up #Dn= , 3 , 3
  608.85  614.35  616.85
     652  655.67  655.67
  608.85  614.35  616.85
     652  655.67  655.67
BR Coef=-1 , 1 , 0 ,0, 0 ,,,0.8,0,1.33,0,
WSPro=,,,, 1 ,,,, 0 ,,,, 0 ,,,,-1 ,-1 ,-1 , 0 , 0 , 0 , 0 , 0
BR U #Sta/Elev= 28
    -350     658       0   655.2      50   654.8     100   654.4     200   653.6
     300   652.7     400   651.8   474.5   651.1   482.5   649.3     484   648.9
     485   648.7   485.1   648.7     492   646.8     495   646.2     500   646.9
     508   647.3   514.9   649.2     515   649.2     516   649.4   517.7   649.9
   525.5   651.8     600   652.4     700   653.2     800   654.1     900   654.8
    1000   655.6    1100   657.6    1120     658
BR U #Mann= 3
    -350     .05     485    .035     515     .05
BC Design=,, 0 ,, 0 ,,,,,,
BC Use User HTab Curves=0
BC User HTab FreeFlow(D)= 0

Type RM Length L Ch R = 1 ,11.151  ,1,1,1
BEGIN DESCRIPTION:
CTH KR / COUNTY LINE ROAD
END DESCRIPTION:
#Sta/Elev= 27
    -350     658       0   655.2      50   654.8     100   654.4     200   653.6
     300   652.7     400   651.8   474.5   651.1   482.5   649.3     484   648.9
     485   648.7   485.1   648.7     492   646.8     495   646.2     500   646.9
     508   647.3   514.9   649.2     515   649.2     516   649.4   517.7   649.9
   525.5   651.8     600   652.4     700   653.2     800   654.1     900   654.8
    1000   655.6    1100   657.6
#Mann= 3 , 0 , 0
    -350     .05       0     485    .035       0     515     .05       0
#XS Ineff= 2 , 0
       0     370     660     635       0     660
Permanent Ineff=
       F       F
Bank Sta=485,515
XS Rating Curve= 0 ,0
Exp/Cntr=0.5,0.3

Type RM Length L Ch R = 1 ,11.141  ,27,27,27
BEGIN DESCRIPTION:
New Section for Ped Bridge
END DESCRIPTION:
#Sta/Elev= 30
     260   657.3  276.17  656.18  289.55  655.64  402.51  654.78  412.57  654.81
  430.84  655.65  451.93  654.97  469.73  653.71  477.39  651.76  479.97  651.68
  486.32   649.8  491.07     647  495.54  646.14  504.66  645.91  508.46   646.1
  511.46  647.17  516.38  649.86  521.99  651.12   525.6  652.94  534.41  654.57
  551.86  656.48  561.62  656.16  567.23  655.04  578.64  653.51  597.71  652.86
  647.97  653.44  702.03  653.37     740  653.95    1240   654.5    1250     660
#Mann= 3 , 0 , 0
     260    .045       0  486.32    .035       0  516.38    .045       0
#XS Ineff= 2 , 0
       0     370             635       0
Permanent Ineff=
       F       F
Bank Sta=486.32,516.38
XS Rating Curve= 0 ,0
Exp/Cntr=0.3,0.1

Type RM Length L Ch R = 3 ,11.14   ,,,
BEGIN DESCRIPTION:
Proposed Ped Bridge at CTH KR
END DESCRIPTION:
Bridge Culvert--1,0,-1,-1, 0
Deck Dist Width WeirC Skew NumUp NumDn MinLoCord MaxHiCord MaxSubmerge Is_Ogee
1,13,2.5,0, 19, 19, , , 0.98, 0, 0,0,,
     370     375     390     405     425     445     465  471.38  471.38  528.62
  528.62     535     555     575   587.5     600   612.5     630    1000
  653.74  653.73  653.83  654.26  655.04  655.63  655.83  655.83  655.83  655.83
  655.83  655.83  655.74  655.48  655.26  655.11  655.09  654.95  652.15
                                                             654     654     654
     654
     370     375     390     405     425     445     465  471.38  471.38  528.62
  528.62     535     555     575   587.5     600   612.5     630    1000
  653.74  653.73  653.83  654.26  655.04  655.63  655.83  655.83  655.83  655.83
  655.83  655.83  655.74  655.48  655.26  655.11  655.09  654.95  652.15
                                                             654     654     654
     654
BR Coef=-1 , 0 , 0 ,, 0 ,,,0.8,0,,1,
WSPro=,,,, 1 ,,,, 0 ,,,, 0 ,,,,-1 ,-1 ,-1 , 0 , 0 , 0 , 0 , 0
BC Design=,, 0 ,, 0 ,,,,,,
BC Use User HTab Curves=0
BC User HTab FreeFlow(D)= 0

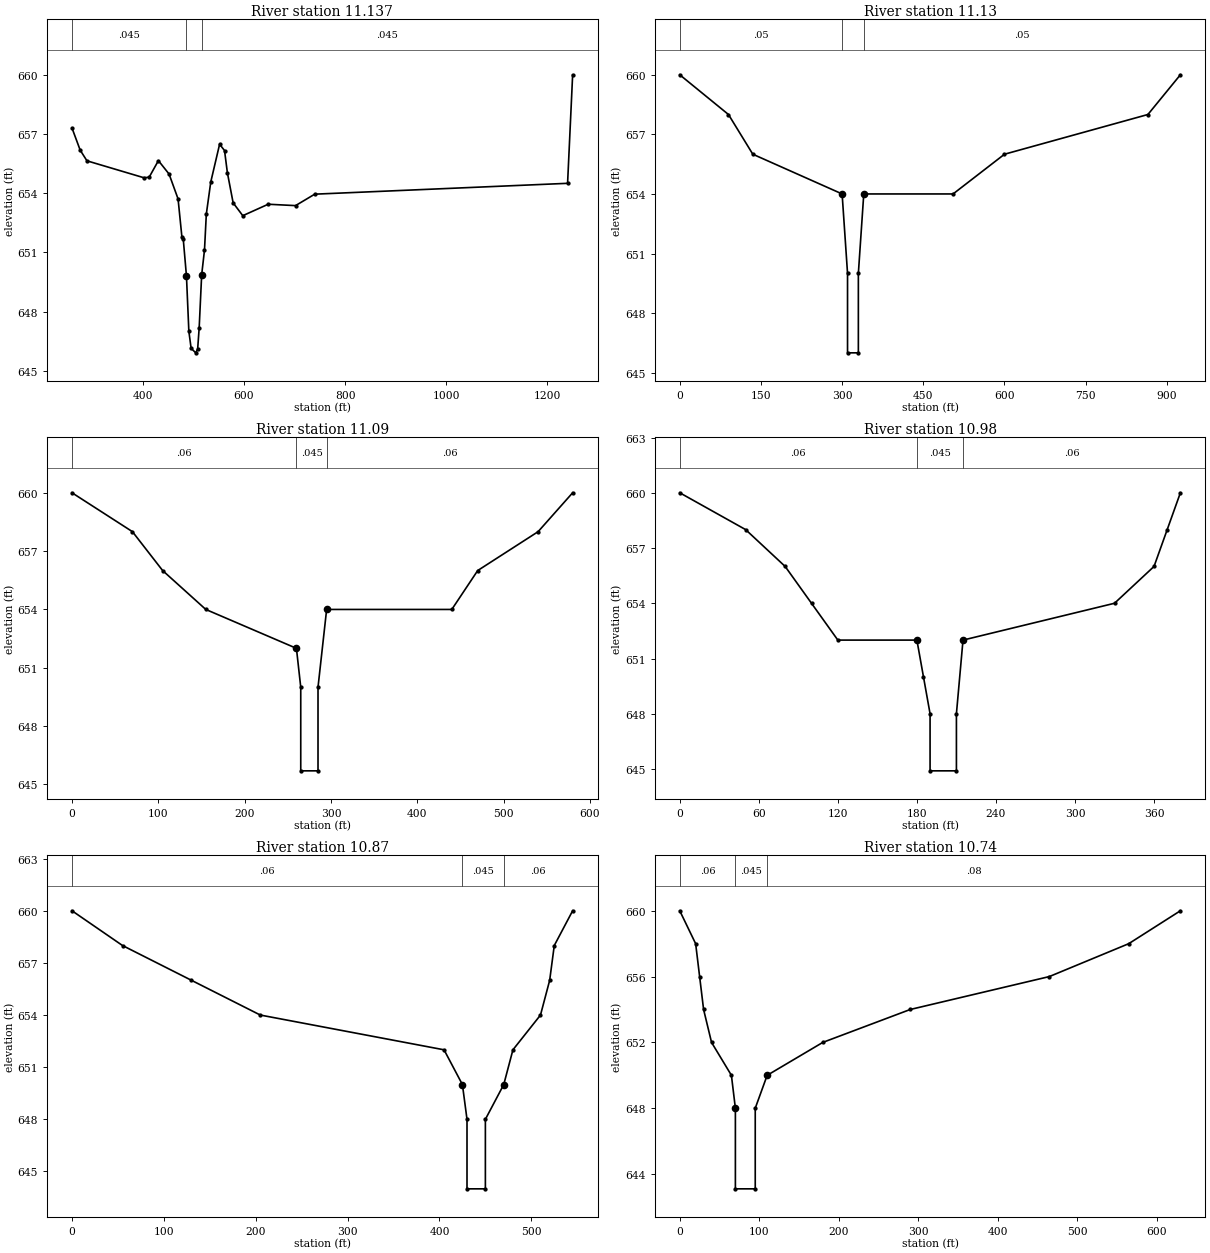
Type RM Length L Ch R = 1 ,11.137  ,40,40,40
BEGIN DESCRIPTION:
Copy of New Section for Ped Bridge
END DESCRIPTION:
#Sta/Elev= 30
     260   657.3  276.17  656.18  289.55  655.64  402.51  654.78  412.57  654.81
  430.84  655.65  451.93  654.97  469.73  653.71  477.39  651.76  479.97  651.68
  486.32   649.8  491.07     647  495.54  646.14  504.66  645.91  508.46   646.1
  511.46  647.17  516.38  649.86  521.99  651.12   525.6  652.94  534.41  654.57
  551.86  656.48  561.62  656.16  567.23  655.04  578.64  653.51  597.71  652.86
  647.97  653.44  702.03  653.37     740  653.95    1240   654.5    1250     660
#Mann= 3 , 0 , 0
     260    .045       0  486.32    .035       0  516.38    .045       0
#XS Ineff= 2 , 0
       0     360             645       0
Permanent Ineff=
       F       F
Bank Sta=486.32,516.38
XS Rating Curve= 0 ,0
Exp/Cntr=0.3,0.1

Type RM Length L Ch R = 1 ,11.13   ,240,240,220
#Sta/Elev= 13
       0     660      90     658     135     656     300     654     310     650
     310     646     330     646     330     650     340     654     505     654
     600     656     865     658     925     660
#Mann= 3 , 0 , 0
       0     .05       0     300    .045       0     340     .05       0
Bank Sta=300,340
XS Rating Curve= 0 ,0
Sediment Elevation=0
Exp/Cntr=0.3,0.1

Type RM Length L Ch R = 1 ,11.09   ,580,570,555
#Sta/Elev= 14
       0     660      70     658     105     656     155     654     260     652
     265     650     265   645.7     285   645.7     285     650     295     654
     440     654     470     656     540     658     580     660
#Mann= 3 , 0 , 0
       0     .06       0     260    .045       0     295     .06       0
Bank Sta=260,295
XS Rating Curve= 0 ,0
Sediment Elevation=0
Exp/Cntr=0.3,0.1

Type RM Length L Ch R = 1 ,10.98   ,580,720,730
#Sta/Elev= 16
       0     660      50     658      80     656     100     654     120     652
     180     652     185     650     190     648     190   644.9     210   644.9
     210     648     215     652     330     654     360     656     370     658
     380     660
#Mann= 3 , 0 , 0
       0     .06       0     180    .045       0     215     .06       0
Bank Sta=180,215
XS Rating Curve= 0 ,0
Sediment Elevation=0
Exp/Cntr=0.3,0.1

Type RM Length L Ch R = 1 ,10.87   ,700,700,640
#Sta/Elev= 16
       0     660      55     658     130     656     205     654     405     652
     425     650     430     648     430     644     450     644     450     648
     470     650     480     652     510     654     520     656     525     658
     545     660
#Mann= 3 , 0 , 0
       0     .06       0     425    .045       0     470     .06       0
Bank Sta=425,470
XS Rating Curve= 0 ,0
Sediment Elevation=0
Exp/Cntr=0.3,0.1

Type RM Length L Ch R = 1 ,10.74   ,720,820,555
#Sta/Elev= 16
       0     660      20     658      25     656      30     654      40     652
      65     650      70     648      70   643.1      95   643.1      95     648
     110     650     180     652     290     654     465     656     565     658
     630     660
#Mann= 3 , 0 , 0
       0     .06       0      70    .045       0     110     .08       0
Bank Sta=70,110
XS Rating Curve= 0 ,0
Sediment Elevation=0
Exp/Cntr=0.3,0.1

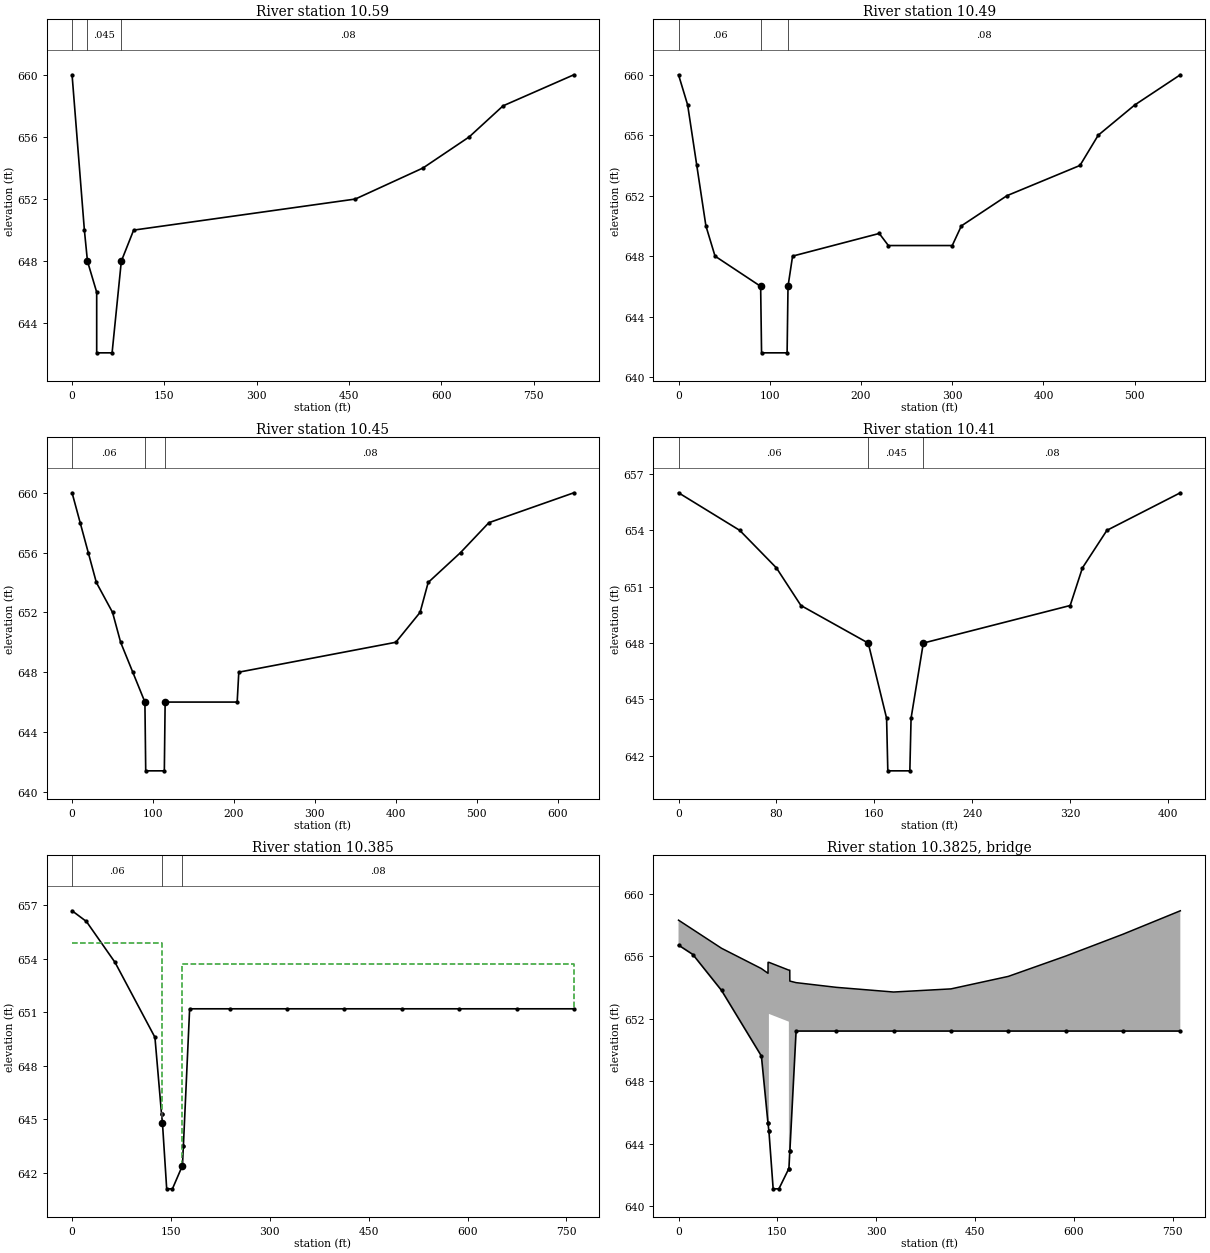
Type RM Length L Ch R = 1 ,10.59   ,555,590,440
#Sta/Elev= 13
       0     660      20     650      25     648      40     646      40   642.1
      65   642.1      80     648     100     650     460     652     570     654
     645     656     700     658     815     660
#Mann= 3 , 0 , 0
       0     .06       0      25    .045       0      80     .08       0
Bank Sta=25,80
XS Rating Curve= 0 ,0
Sediment Elevation=0
Exp/Cntr=0.3,0.1

Type RM Length L Ch R = 1 ,10.49   ,130,220,310
#Sta/Elev= 19
       0     660      10     658      20     654      30     650      40     648
      90     646      91   641.6     119   641.6     120     646     125     648
     220   649.5     230   648.7     300   648.7     310     650     360     652
     440     654     460     656     500     658     550     660
#Mann= 3 , 0 , 0
       0     .06       0      90    .045       0     120     .08       0
Bank Sta=90,120
XS Rating Curve= 0 ,0
Sediment Elevation=0
Exp/Cntr=0.3,0.1

Type RM Length L Ch R = 1 ,10.45   ,220,310,220
#Sta/Elev= 19
       0     660      10     658      20     656      30     654      50     652
      60     650      75     648      90     646      91   641.4     114   641.4
     115     646     204     646     206     648     400     650     430     652
     440     654     480     656     515     658     620     660
#Mann= 3 , 0 , 0
       0     .06       0      90    .045       0     115     .08       0
Bank Sta=90,115
XS Rating Curve= 0 ,0
Sediment Elevation=0
Exp/Cntr=0.3,0.1

Type RM Length L Ch R = 1 ,10.41   ,160,135,150
#Sta/Elev= 14
       0     656      50     654      80     652     100     650     155     648
     170     644     171   641.2     189   641.2     190     644     200     648
     320     650     330     652     350     654     410     656
#Mann= 3 , 0 , 0
       0     .06       0     155    .045       0     200     .08       0
Bank Sta=155,200
XS Rating Curve= 0 ,0
Sediment Elevation=0
Exp/Cntr=0.3,0.1

Type RM Length L Ch R = 1 ,10.385  ,43,43,43
BEGIN DESCRIPTION:
This is a REPEATED section.
END DESCRIPTION:
#Sta/Elev= 22
       0   656.7   21.75   656.1   65.25   653.8 125.715   649.6  135.72   645.3
 135.807   645.3 137.025   644.8 137.112   644.8  143.55   641.1  152.25   641.1
 167.388   642.4 167.475   642.4  168.78   643.5 168.867   643.5  178.35   651.2
  239.25   651.2  326.25   651.2  413.25   651.2  500.25   651.2  587.25   651.2
  674.25   651.2  761.25   651.2
#Mann= 3 , 0 , 0
       0     .06       0 137.025    .035       0 167.475     .08       0
#XS Ineff= 2 , 0
         137.025   654.9 167.475           653.7
Permanent Ineff=
       F       F
Bank Sta=137.025,167.475
XS Rating Curve= 0 ,0
Sediment Elevation=0
Exp/Cntr=0.5,0.3

Type RM Length L Ch R = 3 ,10.3825 ,,,
BEGIN DESCRIPTION:
Bridge #3
END DESCRIPTION:
Bridge Culvert--1,0,-1,-1, 0
Deck Dist Width WeirC Skew NumUp NumDn MinLoCord MaxHiCord MaxSubmerge Is_Ogee
10,23,2.5,0, 20, 20, 653.7, , 0.98, 0, 0,0,,
       0   21.75   65.25 125.715  135.72 135.807 137.025 137.112 167.388 167.475
  168.78 168.867  178.35  239.25  326.25  413.25  500.25  587.25  674.25  761.25
   658.3   657.7   656.5   655.2   654.9   655.6   655.6   655.6   655.1   655.1
   655.1   654.4   654.3     654   653.7   653.9   654.7     656   657.4   658.9
   656.7   656.1   653.8   649.6   645.3   645.3   644.8   652.3   651.8   642.4
   643.5   643.5   651.2   651.2   651.2   651.2   651.2   651.2   651.2   651.2
       0   21.75   65.25 125.715  135.72 135.807 137.025 137.112 167.388 167.475
  168.78 168.867  178.35  239.25  326.25  413.25  500.25  587.25  674.25  761.25
   658.3   657.7   656.5   655.2   654.9   655.6   655.6   655.6   655.1   655.1
   655.1   654.4   654.3     654   653.7   653.9   654.7     656   657.4   658.9
   656.7   656.1   653.8   649.6   645.3   645.3   644.8   652.3   651.8   642.4
   643.5   643.5   651.2   651.2   651.2   651.2   651.2   651.2   651.2   651.2
BR Coef=-1 , 0 , 0 ,0, 0 ,,,0.8,0,,1,
WSPro=,,,, 1 ,,,, 0 ,,,, 0 ,,,,-1 ,-1 ,-1 , 0 , 0 , 0 , 0 , 0
BC Design=,, 0 ,, 0 ,,,,,,
BC Use User HTab Curves=0
BC User HTab FreeFlow(D)= 0

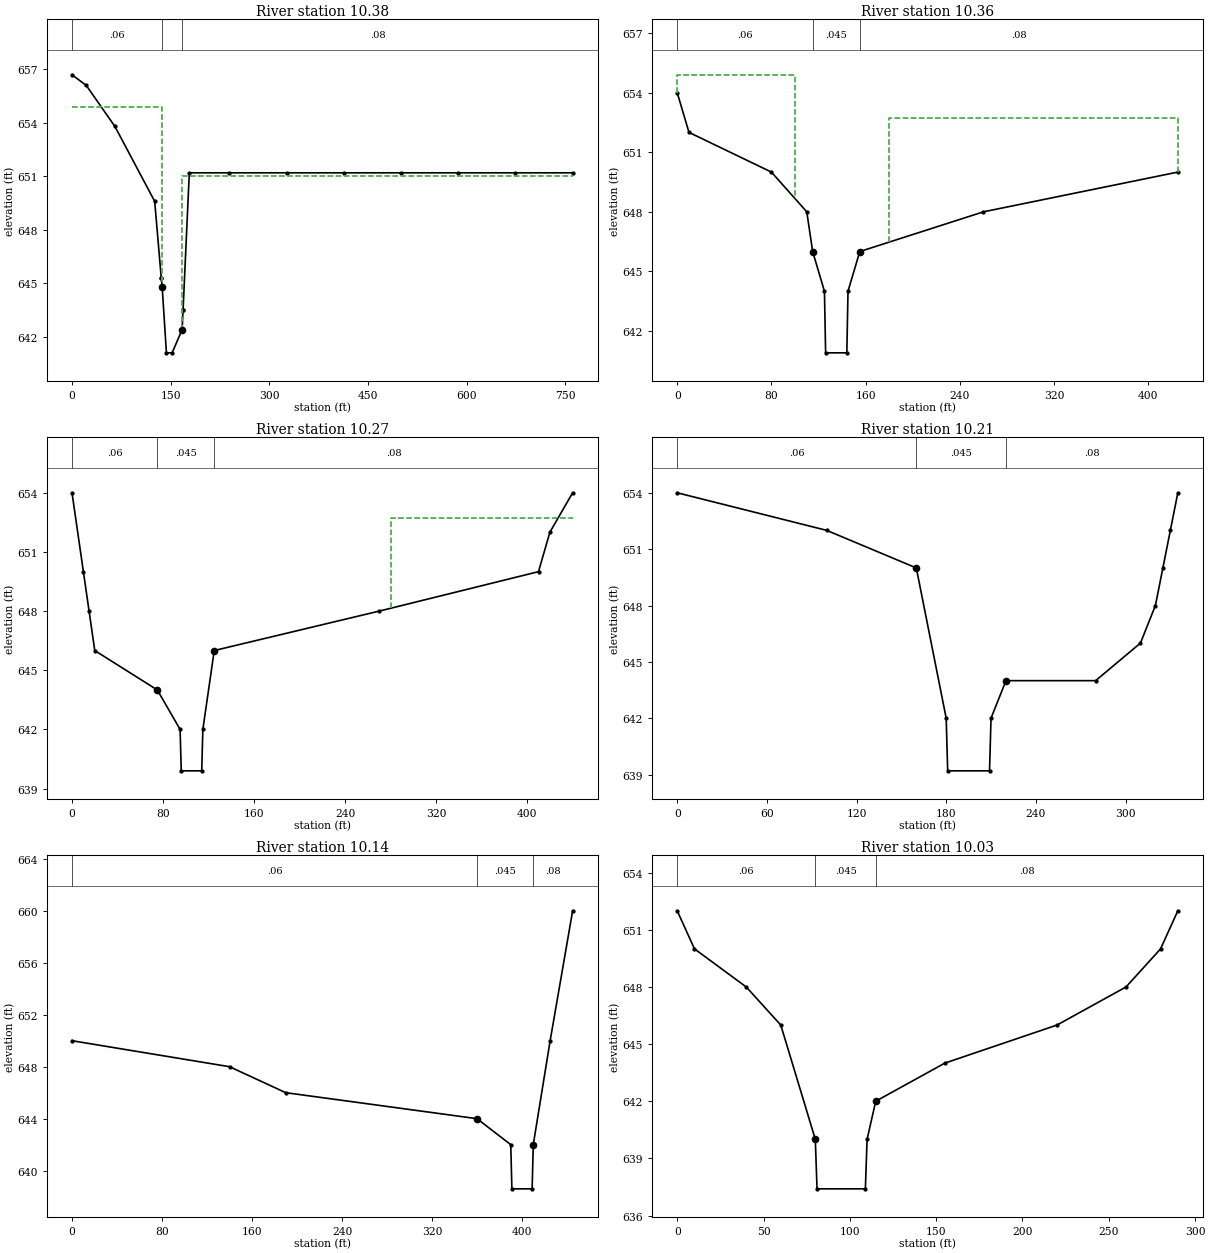
Type RM Length L Ch R = 1 ,10.38   ,75,75,75
BEGIN DESCRIPTION:
STH 31 / GREEN BAY ROAD
END DESCRIPTION:
#Sta/Elev= 22
       0   656.7   21.75   656.1   65.25   653.8 125.715   649.6  135.72   645.3
 135.807   645.3 137.025   644.8 137.112   644.8  143.55   641.1  152.25   641.1
 167.388   642.4 167.475   642.4  168.78   643.5 168.867   643.5  178.35   651.2
  239.25   651.2  326.25   651.2  413.25   651.2  500.25   651.2  587.25   651.2
  674.25   651.2  761.25   651.2
#Mann= 3 , 0 , 0
       0     .06       0 137.025    .035       0 167.475     .08       0
#XS Ineff= 2 , 0
       0 137.025   654.9 167.475       0     651
Permanent Ineff=
       F       F
Bank Sta=137.025,167.475
XS Rating Curve= 0 ,0
Sediment Elevation=0
Exp/Cntr=0.5,0.3

Type RM Length L Ch R = 1 ,10.36   ,500,555,380
#Sta/Elev= 12
       0     654      10     652      80     650     110     648     115     646
     125     644     126   640.9     144   640.9     145     644     155     646
     260     648     425     650
#Mann= 3 , 0 , 0
       0     .06       0     115    .045       0     155     .08       0
#XS Ineff= 2 , 0
       0     100   654.9     180       0   652.7
Permanent Ineff=
       F       F
Bank Sta=115,155
XS Rating Curve= 0 ,0
Exp/Cntr=0.3,0.1

Type RM Length L Ch R = 1 ,10.27   ,320,430,455
#Sta/Elev= 14
       0     654      10     650      15     648      20     646      75     644
      95     642      96   639.9     114   639.9     115     642     125     646
     270     648     410     650     420     652     440     654
#Mann= 3 , 0 , 0
       0     .06       0      75    .045       0     125     .08       0
#XS Ineff= 2 , 0
       0                     280       0   652.7
Permanent Ineff=
       F       F
Bank Sta=75,125
XS Rating Curve= 0 ,0
Exp/Cntr=0.3,0.1

Type RM Length L Ch R = 1 ,10.21   ,330,440,440
#Sta/Elev= 14
       0     654     100     652     160     650     180     642     181   639.2
     209   639.2     210     642     220     644     280     644     310     646
     320     648     325     650     330     652     335     654
#Mann= 3 , 0 , 0
       0     .06       0     160    .045       0     220     .08       0
Bank Sta=160,220
XS Rating Curve= 0 ,0
Exp/Cntr=0.3,0.1

Type RM Length L Ch R = 1 ,10.14   ,580,640,530
#Sta/Elev= 10
       0     650     140     648     190     646     360     644     390     642
     391   638.6     409   638.6     410     642     425     650     445     660
#Mann= 3 , 0 , 0
       0     .06       0     360    .045       0     410     .08       0
Bank Sta=360,410
XS Rating Curve= 0 ,0
Exp/Cntr=0.3,0.1

Type RM Length L Ch R = 1 ,10.03   ,270,240,255
#Sta/Elev= 14
       0     652      10     650      40     648      60     646      80     640
      81   637.4     109   637.4     110     640     115     642     155     644
     220     646     260     648     280     650     290     652
#Mann= 3 , 0 , 0
       0     .06       0      80    .045       0     115     .08       0
Bank Sta=80,115
XS Rating Curve= 0 ,0
Exp/Cntr=0.3,0.1

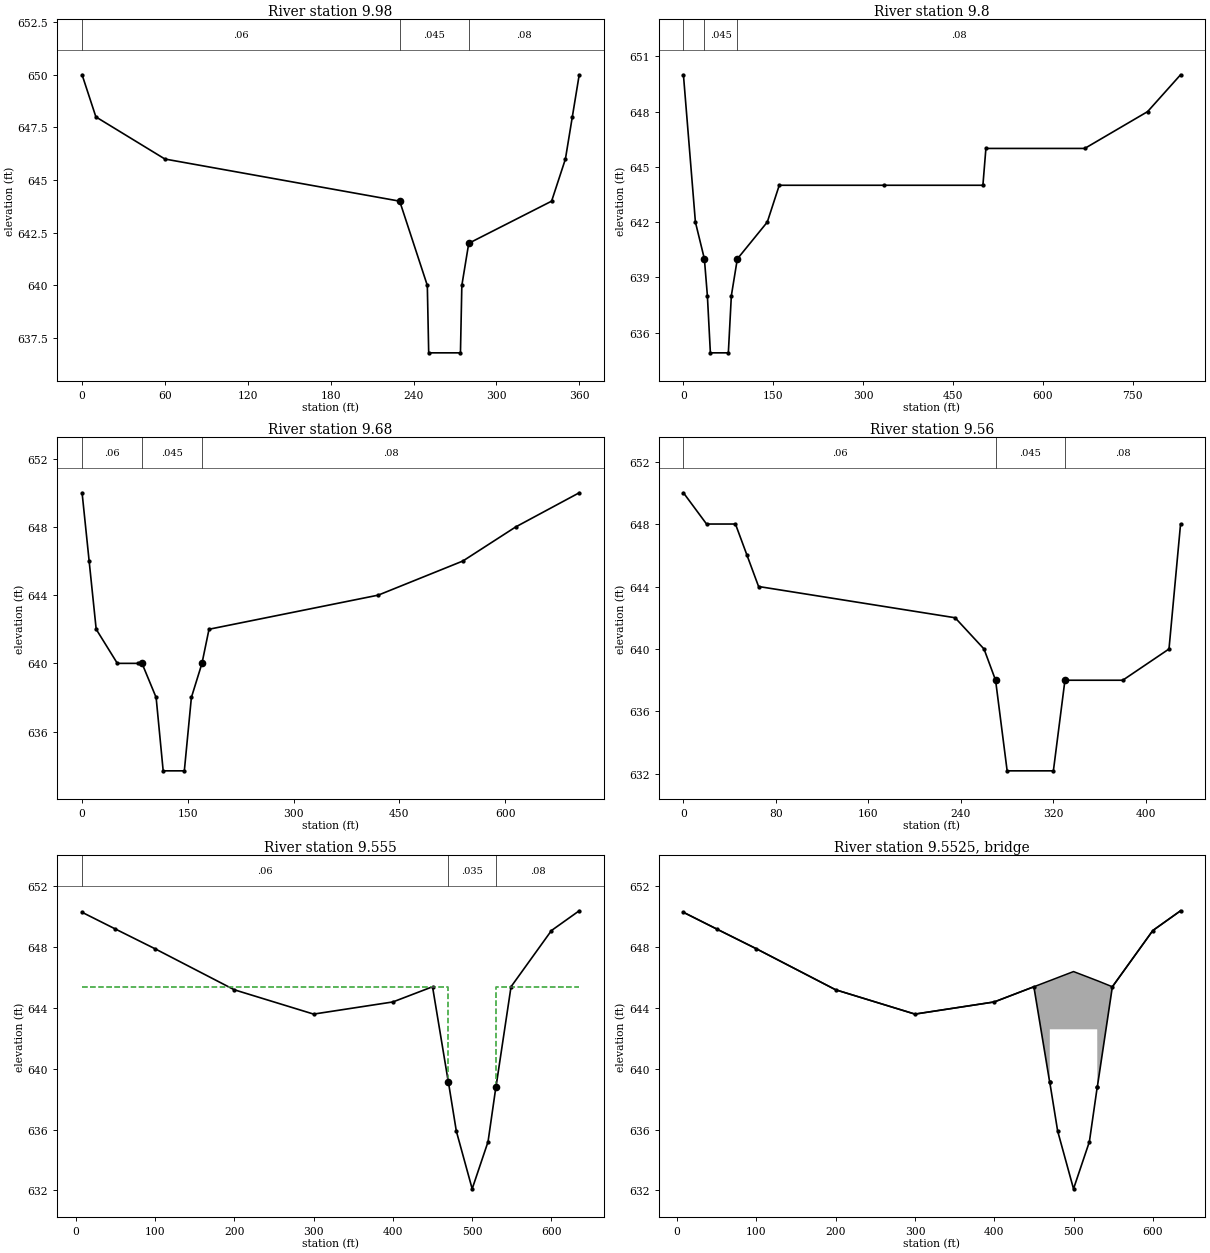
Type RM Length L Ch R = 1 ,9.98    ,800,1020,440
#Sta/Elev= 13
       0     650      10     648      60     646     230     644     250     640
     251   636.8     274   636.8     275     640     280     642     340     644
     350     646     355     648     360     650
#Mann= 3 , 0 , 0
       0     .06       0     230    .045       0     280     .08       0
Bank Sta=230,280
XS Rating Curve= 0 ,0
Exp/Cntr=0.3,0.1

Type RM Length L Ch R = 1 ,9.8     ,670,655,440
#Sta/Elev= 16
       0     650      20     642      35     640      40     638      45   634.9
      75   634.9      80     638      90     640     140     642     160     644
     335     644     500     644     505     646     670     646     775     648
     830     650
#Mann= 3 , 0 , 0
       0     .06       0      35    .045       0      90     .08       0
Bank Sta=35,90
XS Rating Curve= 0 ,0
Exp/Cntr=0.3,0.1

Type RM Length L Ch R = 1 ,9.68    ,490,640,770
#Sta/Elev= 16
       0     650      10     646      20     642      50     640      80     640
      85     640     105     638     115   633.7     145   633.7     155     638
     170     640     180     642     420     644     540     646     615     648
     705     650
#Mann= 3 , 0 , 0
       0     .06       0      85    .045       0     170     .08       0
Bank Sta=85,170
XS Rating Curve= 0 ,0
Exp/Cntr=0.3,0.1

Type RM Length L Ch R = 1 ,9.56    ,116,56,86
#Sta/Elev= 14
       0     650      20     648      45     648      55     646      65     644
     235     642     260     640     270     638     280   632.2     320   632.2
     330     638     380     638     420     640     430     648
#Mann= 3 , 0 , 0
       0     .06       0     270    .045       0     330     .08       0
Bank Sta=270,330
XS Rating Curve= 0 ,0
Exp/Cntr=0.3,0.1

Type RM Length L Ch R = 1 ,9.555   ,34,34,34
BEGIN DESCRIPTION:
This is a REPEATED section.
END DESCRIPTION:
#Sta/Elev= 17
       8   650.3      50   649.2     100   647.9     200   645.2     300   643.6
     400   644.4     450   645.4     470   639.1   470.1   639.1     480   635.9
     500   632.1     520   635.2   529.9   638.8     530   638.8     549   645.4
     600   649.1     635   650.4
#Mann= 3 , 0 , 0
       8     .06       0     470    .035       0     530     .08       0
#XS Ineff= 2 , 0
       0     470   645.4     530       0   645.4
Permanent Ineff=
       F       F
Bank Sta=470,530
XS Rating Curve= 0 ,0
Exp/Cntr=0.5,0.3

Type RM Length L Ch R = 3 ,9.5525  ,,,
BEGIN DESCRIPTION:
Bridge #2
END DESCRIPTION:
Bridge Culvert--1,0,-1,-1, 0
Deck Dist Width WeirC Skew NumUp NumDn MinLoCord MaxHiCord MaxSubmerge Is_Ogee
5.5,23,3,0, 17, 17, 643.6, , 0.98, 0, 0,0,,
       8      50     100     200     300     400     450     470   470.1     480
     500     520   529.9     530     549     600     635
   650.3   649.2   647.9   645.2   643.6   644.4   645.4   645.8   645.8     646
   646.4     646   645.8   645.8   645.4   649.1   650.4
   650.3   649.2   647.9   645.2   643.6   644.4   645.4   639.1   642.6   642.6
   642.6   642.6   642.6   638.8   645.4   649.1   650.4
       8      50     100     200     300     400     450     470   470.1     480
     500     520   529.9     530     549     600     635
   650.3   649.2   647.9   645.2   643.6   644.4   645.4   645.8   645.8     646
   646.4     646   645.8   645.8   645.4   649.1   650.4
   650.3   649.2   647.9   645.2   643.6   644.4   645.4   639.1   642.6   642.6
   642.6   642.6   642.6   638.8   645.4   649.1   650.4
BR Coef=-1 , 0 , 0 ,0, 0 ,,,0.8,0,,1,
WSPro=,,,, 1 ,,,, 0 ,,,, 0 ,,,,-1 ,-1 ,-1 , 0 , 0 , 0 , 0 , 0
BC Design=,, 0 ,, 0 ,,,,,,
BC Use User HTab Curves=0
BC User HTab FreeFlow(D)= 0

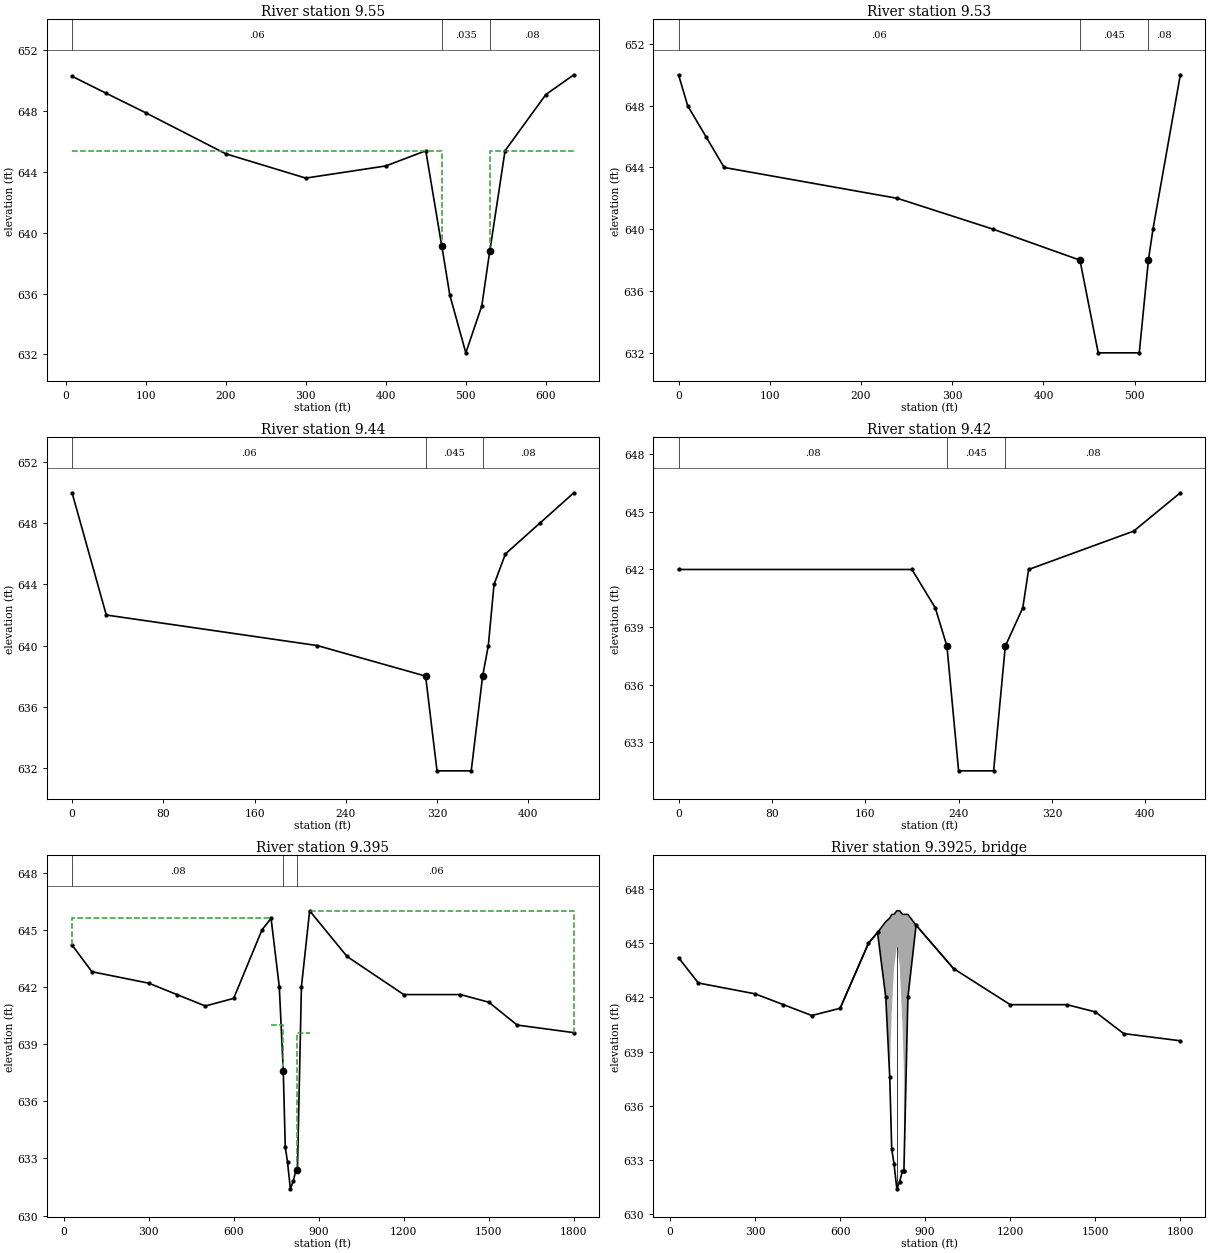
Type RM Length L Ch R = 1 ,9.55    ,90,90,90
BEGIN DESCRIPTION:
CTH A / 7TH STREET
END DESCRIPTION:
#Sta/Elev= 17
       8   650.3      50   649.2     100   647.9     200   645.2     300   643.6
     400   644.4     450   645.4     470   639.1   470.1   639.1     480   635.9
     500   632.1     520   635.2   529.9   638.8     530   638.8     549   645.4
     600   649.1     635   650.4
#Mann= 3 , 0 , 0
       8     .06       0     470    .035       0     530     .08       0
#XS Ineff= 2 , 0
       0     470   645.4     530       0   645.4
Permanent Ineff=
       F       F
Bank Sta=470,530
XS Rating Curve= 0 ,0
Exp/Cntr=0.5,0.3

Type RM Length L Ch R = 1 ,9.53    ,440,530,555
#Sta/Elev= 12
       0     650      10     648      30     646      50     644     240     642
     345     640     440     638     460     632     505     632     515     638
     520     640     550     650
#Mann= 3 , 0 , 0
       0     .06       0     440    .045       0     515     .08       0
Bank Sta=440,515
XS Rating Curve= 0 ,0
Exp/Cntr=0.3,0.1

Type RM Length L Ch R = 1 ,9.44    ,170,140,130
#Sta/Elev= 12
       0     650      30     642     215     640     310     638     320   631.8
     350   631.8     360     638     365     640     370     644     380     646
     410     648     440     650
#Mann= 3 , 0 , 0
       0     .06       0     310    .045       0     360     .08       0
Bank Sta=310,360
XS Rating Curve= 0 ,0
Exp/Cntr=0.3,0.1

Type RM Length L Ch R = 1 ,9.42    ,95,125,145
#Sta/Elev= 11
       0     642     200     642     220     640     230     638     240   631.5
     270   631.5     280     638     295     640     300     642     390     644
     430     646
#Mann= 3 , 0 , 0
       0     .08       0     230    .045       0     280     .08       0
Bank Sta=230,280
XS Rating Curve= 0 ,0
Exp/Cntr=0.3,0.1

Type RM Length L Ch R = 1 ,9.395   ,44.2,44.2,44.2
BEGIN DESCRIPTION:
This is a REPEATED section.
END DESCRIPTION:
#Sta/Elev= 25
      30   644.2     100   642.8     300   642.2     400   641.6     500     641
     600   641.4     700     645     732   645.6     761     642     775   637.6
     782   633.6     790   632.8     800   631.4     810   631.8     820   632.4
   824.9   632.4     825   632.4     839     642     868     646    1000   643.6
    1200   641.6    1400   641.6    1500   641.2    1600     640    1800   639.6
#Mann= 3 , 0 , 0
      30     .08       0     775    .035       0     825     .06       0
#XS Ineff= 4 ,-1
       0     732   645.6     732     775     640     825     868   639.6
     868    2000     646
Permanent Ineff=
       F       F       F       F
Bank Sta=775,825
XS Rating Curve= 0 ,0
Exp/Cntr=0.5,0.3

Type RM Length L Ch R = 3 ,9.3925  ,,,
BEGIN DESCRIPTION:
Bridge #1
END DESCRIPTION:
Bridge Culvert--1,0,-1,-1, 0
Deck Dist Width WeirC Skew NumUp NumDn MinLoCord MaxHiCord MaxSubmerge Is_Ogee
23,10.6,2.8,0, 15, 15, 641.4, , 0.98, 0, 0,0,,
     600     700     732     761     775     782     790     800     810     820
   824.9     825     839     868    1000
   641.4     645   645.6   646.2   646.4   646.6   646.6   646.8   646.8   646.6
   646.6   646.6   646.6     646   643.6
   641.4     645   645.6     642   637.6   641.2   643.6   644.8   643.8   640.4
     638   632.4     642     646   643.6
     600     700     732     761     775     782     790     800     810     820
   824.9     825     839     868    1000
   641.4     645   645.6   646.2   646.4   646.6   646.6   646.8   646.8   646.6
   646.6   646.6   646.6     646   643.6
   641.4     645   645.6     642   637.6   641.2   643.6   644.8   643.8   640.4
     638   632.4     642     646   643.6
Pier Skew, UpSta & Num, DnSta & Num=  ,800, 2 ,800, 2 , 0 , 0 , 0 ,,
      .1      .1
   631.4   644.8
      .1      .1
   631.4   644.8
BR Coef= 1 , 0 , 0 ,0.9, 0 ,,,0.8,0,,1,
WSPro=,,,, 1 ,,,, 0 ,,,, 0 ,,,,-1 ,-1 ,-1 , 0 , 0 , 0 , 0 , 0
BC Design=,, 0 ,, 0 ,,,,,,
BC Use User HTab Curves=0
BC User HTab FreeFlow(D)= 0