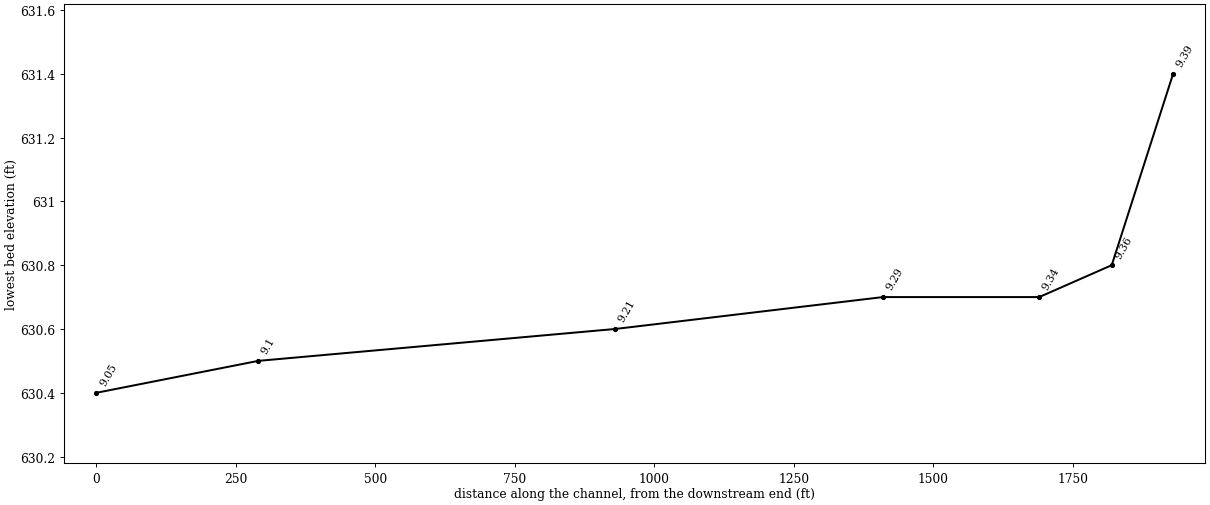
HEC-RAS study B30_143_144.prj: Pike River

--- B30_143_144.g10 (geometry) --- (continued)

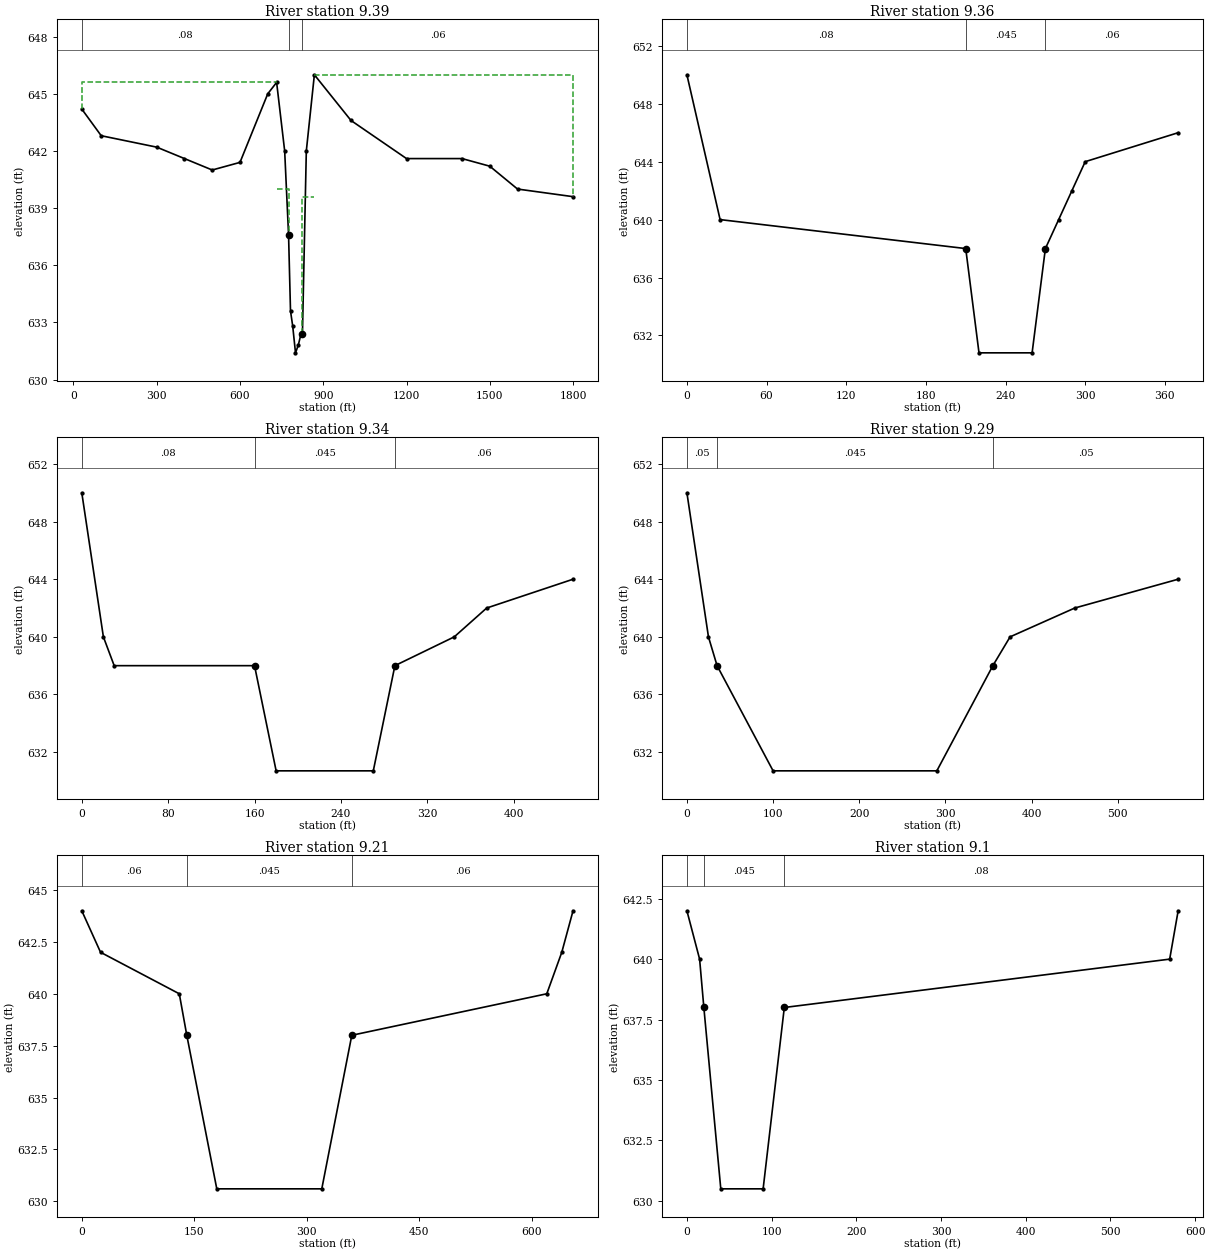
Type RM Length L Ch R = 1 ,9.39    ,140,110,50
BEGIN DESCRIPTION:
PETRIFYING SPRINGS PARK DR
END DESCRIPTION:
#Sta/Elev= 25
      30   644.2     100   642.8     300   642.2     400   641.6     500     641
     600   641.4     700     645     732   645.6     761     642     775   637.6
     782   633.6     790   632.8     800   631.4     810   631.8     820   632.4
   824.9   632.4     825   632.4     839     642     868     646    1000   643.6
    1200   641.6    1400   641.6    1500   641.2    1600     640    1800   639.6
#Mann= 3 , 0 , 0
      30     .08       0     775    .035       0     825     .06       0
#XS Ineff= 4 ,-1
       0     732   645.6     732     775     640     825     868   639.6
     868    2000     646
Permanent Ineff=
       F       F       F       F
Bank Sta=775,825
XS Rating Curve= 0 ,0
Exp/Cntr=0.5,0.3

Type RM Length L Ch R = 1 ,9.36    ,220,130,130
#Sta/Elev= 10
       0     650      25     640     210     638     220   630.8     260   630.8
     270     638     280     640     290     642     300     644     370     646
#Mann= 3 , 0 , 0
       0     .08       0     210    .045       0     270     .06       0
Bank Sta=210,270
XS Rating Curve= 0 ,0
Exp/Cntr=0.3,0.1

Type RM Length L Ch R = 1 ,9.34    ,490,280,240
#Sta/Elev= 10
       0     650      20     640      30     638     160     638     180   630.7
     270   630.7     290     638     345     640     375     642     455     644
#Mann= 3 , 0 , 0
       0     .08       0     160    .045       0     290     .06       0
Bank Sta=160,290
XS Rating Curve= 0 ,0
Exp/Cntr=0.3,0.1

Type RM Length L Ch R = 1 ,9.29    ,380,480,610
#Sta/Elev= 9
       0     650      25     640      35     638     100   630.7     290   630.7
     355     638     375     640     450     642     570     644
#Mann= 3 , 0 , 0
       0     .05       0      35    .045       0     355     .05       0
Bank Sta=35,355
XS Rating Curve= 0 ,0
Exp/Cntr=0.3,0.1

Type RM Length L Ch R = 1 ,9.21    ,610,640,580
#Sta/Elev= 10
       0     644      25     642     130     640     140     638     180   630.6
     320   630.6     360     638     620     640     640     642     655     644
#Mann= 3 , 0 , 0
       0     .06       0     140    .045       0     360     .06       0
Bank Sta=140,360
XS Rating Curve= 0 ,0
Exp/Cntr=0.3,0.1

Type RM Length L Ch R = 1 ,9.1     ,300,290,230
#Sta/Elev= 8
       0     642      15     640      20     638      40   630.5      90   630.5
     115     638     570     640     580     642
#Mann= 3 , 0 , 0
       0     .06       0      20    .045       0     115     .08       0
Bank Sta=20,115
XS Rating Curve= 0 ,0
Exp/Cntr=0.3,0.1

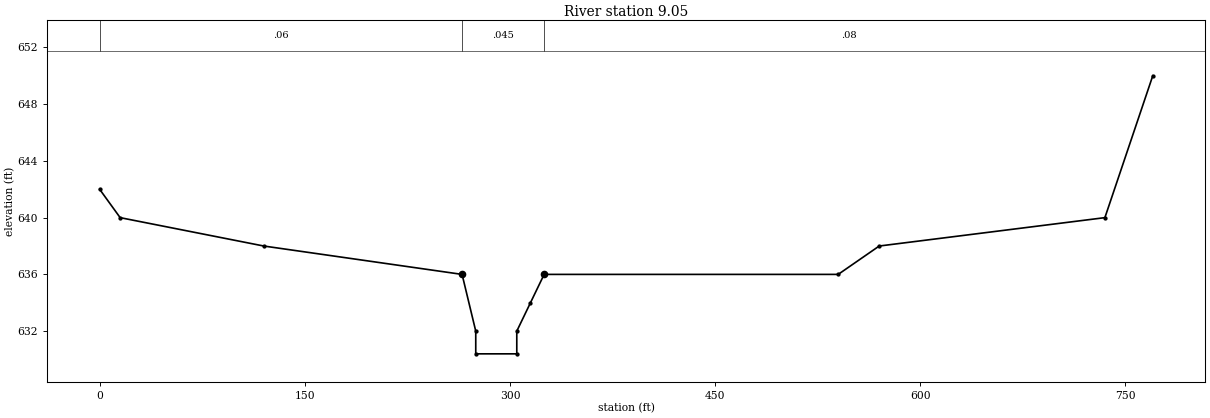
Type RM Length L Ch R = 1 ,9.05    ,555,800,910
#Sta/Elev= 14
       0     642      15     640     120     638     265     636     275     632
     275   630.4     305   630.4     305     632     315     634     325     636
     540     636     570     638     735     640     770     650
#Mann= 3 , 0 , 0
       0     .06       0     265    .045       0     325     .08       0
Bank Sta=265,325
XS Rating Curve= 0 ,0
Exp/Cntr=0.3,0.1
LCMann Table=0

Chan Stop Cuts=-1
Use User Specified Reach Order=0
Composite Channel Slope=5

--- B30_143_144.g01 (geometry) ---

Geom Title=Existing Condition - Corrected
Program Version=4.10

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
River Reach=RIVER-1         ,Reach-1

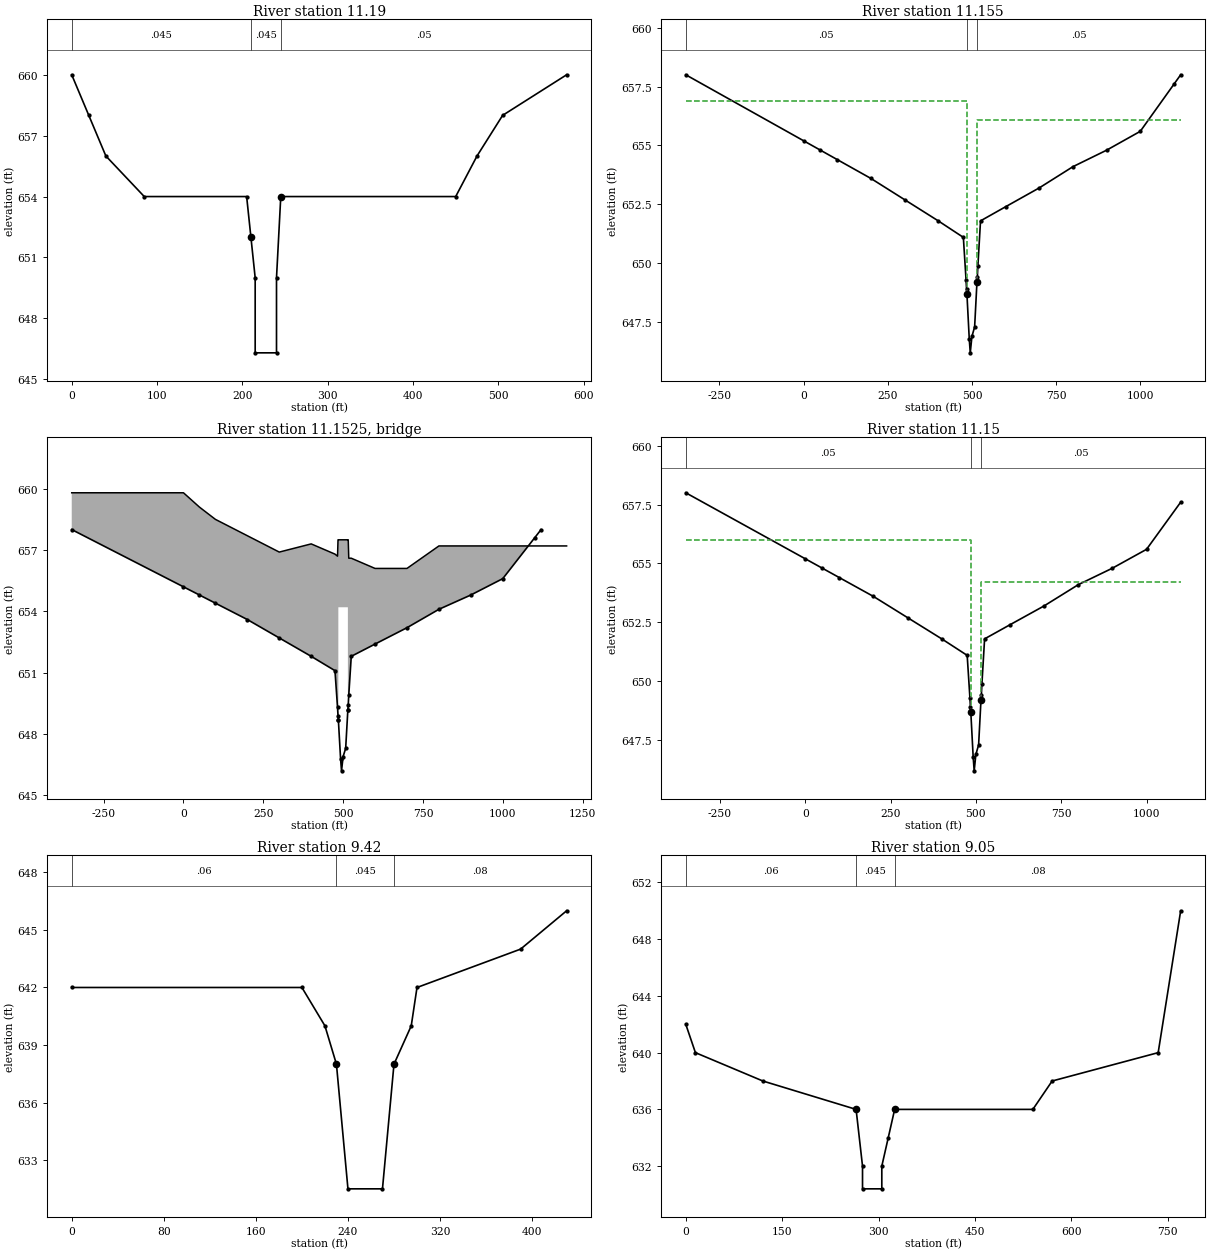
Type RM Length L Ch R = 1 ,11.19   ,160,160,170
#Sta/Elev= 15
       0     660      20     658      40     656      85     654     205     654
     210     652     215     650     215   646.3     240   646.3     240     650
     245     654     450     654     475     656     505     658     580     660
#Mann= 3 , 0 , 0
       0    .045       0     210    .045       0     245     .05       0
Bank Sta=210,245
XS Rating Curve= 0 ,0
Sediment Elevation=0
Exp/Cntr=0.3,0.1

Type RM Length L Ch R = 1 ,11.155  ,23,23,23
BEGIN DESCRIPTION:
This is a REPEATED section.
END DESCRIPTION:
#Sta/Elev= 28
    -350     658       0   655.2      50   654.8     100   654.4     200   653.6
     300   652.7     400   651.8   474.5   651.1   482.5   649.3     484   648.9
     485   648.7   485.1   648.7     492   646.8     495   646.2     500   646.9
     508   647.3   514.9   649.2     515   649.2     516   649.4   517.7   649.9
   525.5   651.8     600   652.4     700   653.2     800   654.1     900   654.8
    1000   655.6    1100   657.6    1120     658
#Mann= 3 , 0 , 0
    -350     .05       0     485    .035       0     515     .05       0
#XS Ineff= 2 , 0
             485   656.9     515           656.1
Permanent Ineff=
       F       F
Bank Sta=485,515
XS Rating Curve= 0 ,0
Sediment Elevation=0
Exp/Cntr=0.5,0.3

Type RM Length L Ch R = 3 ,11.1525 ,,,
BEGIN DESCRIPTION:
Bridge #4
Culvert at CTH KR
END DESCRIPTION:
Bridge Culvert--1,0,-1,-1, 0
Deck Dist Width WeirC Skew NumUp NumDn MinLoCord MaxHiCord MaxSubmerge Is_Ogee
1,21,2.5,0, 21, 21, 656.1, , 0.98, 0, 0,0,,
    -350       0      50     100     200     300     400   474.5   482.5     484
     485   485.1   514.9     515     516   517.7   525.5     600     700     800
    1200
   659.8   659.8   659.1   658.5   657.7   656.9   657.3   656.8   656.7   657.5
   657.5   657.5   657.5   657.5   657.5   656.6   656.6   656.1   656.1   657.2
   657.2
           655.2   654.8   654.4   653.6   652.7   651.8   651.1   649.3   648.9
   648.7   654.2   654.2   649.2   649.4   649.9   651.8   652.4   653.2   654.1
        
    -350       0      50     100     200     300     400   474.5   482.5     484
     485   485.1   514.9     515     516   517.7   525.5     600     700     800
    1200
   659.8   659.8   659.1   658.5   657.7   656.9   657.3   656.8   656.7   657.5
   657.5   657.5   657.5   657.5   657.5   656.6   656.6   656.1   656.1   657.2
   657.2
           655.2   654.8   654.4   653.6   652.7   651.8   651.1   649.3   648.9
   648.7   654.2   654.2   649.2   649.4   649.9   651.8   652.4   653.2   654.1
        
BR Coef=-1 , 0 , 0 ,0, 0 ,,,0.8,0,,1,
WSPro=,,,, 1 ,,,, 0 ,,,, 0 ,,,,-1 ,-1 ,-1 , 0 , 0 , 0 , 0 , 0
BC Design=,, 0 ,, 0 ,,,,,,
BC Use User HTab Curves=0
BC User HTab FreeFlow(D)= 0

Type RM Length L Ch R = 1 ,11.15   ,105,105,105
BEGIN DESCRIPTION:
CTH KR / COUNTY LINE ROAD
END DESCRIPTION:
#Sta/Elev= 27
    -350     658       0   655.2      50   654.8     100   654.4     200   653.6
     300   652.7     400   651.8   474.5   651.1   482.5   649.3     484   648.9
     485   648.7   485.1   648.7     492   646.8     495   646.2     500   646.9
     508   647.3   514.9   649.2     515   649.2     516   649.4   517.7   649.9
   525.5   651.8     600   652.4     700   653.2     800   654.1     900   654.8
    1000   655.6    1100   657.6
#Mann= 3 , 0 , 0
    -350     .05       0     485    .035       0     515     .05       0
#XS Ineff= 2 , 0
             485     656     515           654.2
Permanent Ineff=
       F       F
Bank Sta=485,515
XS Rating Curve= 0 ,0
Sediment Elevation=0
Exp/Cntr=0.5,0.3

Type RM Length L Ch R = 1 ,9.42    ,95,125,145
#Sta/Elev= 11
       0     642     200     642     220     640     230     638     240   631.5
     270   631.5     280     638     295     640     300     642     390     644
     430     646
#Mann= 3 , 0 , 0
       0     .06       0     230    .045       0     280     .08       0
Bank Sta=230,280
XS Rating Curve= 0 ,0
Exp/Cntr=0.3,0.1

Type RM Length L Ch R = 1 ,9.05    ,555,800,910
#Sta/Elev= 14
       0     642      15     640     120     638     265     636     275     632
     275   630.4     305   630.4     305     632     315     634     325     636
     540     636     570     638     735     640     770     650
#Mann= 3 , 0 , 0
       0     .06       0     265    .045       0     325     .08       0
Bank Sta=265,325
XS Rating Curve= 0 ,0
Exp/Cntr=0.3,0.1

--- B30_143_144.g02 (geometry) ---

Geom Title=WisDOT Corrected existing-- August 2018
Program Version=5.03

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
River Reach=RIVER-1         ,Reach-1

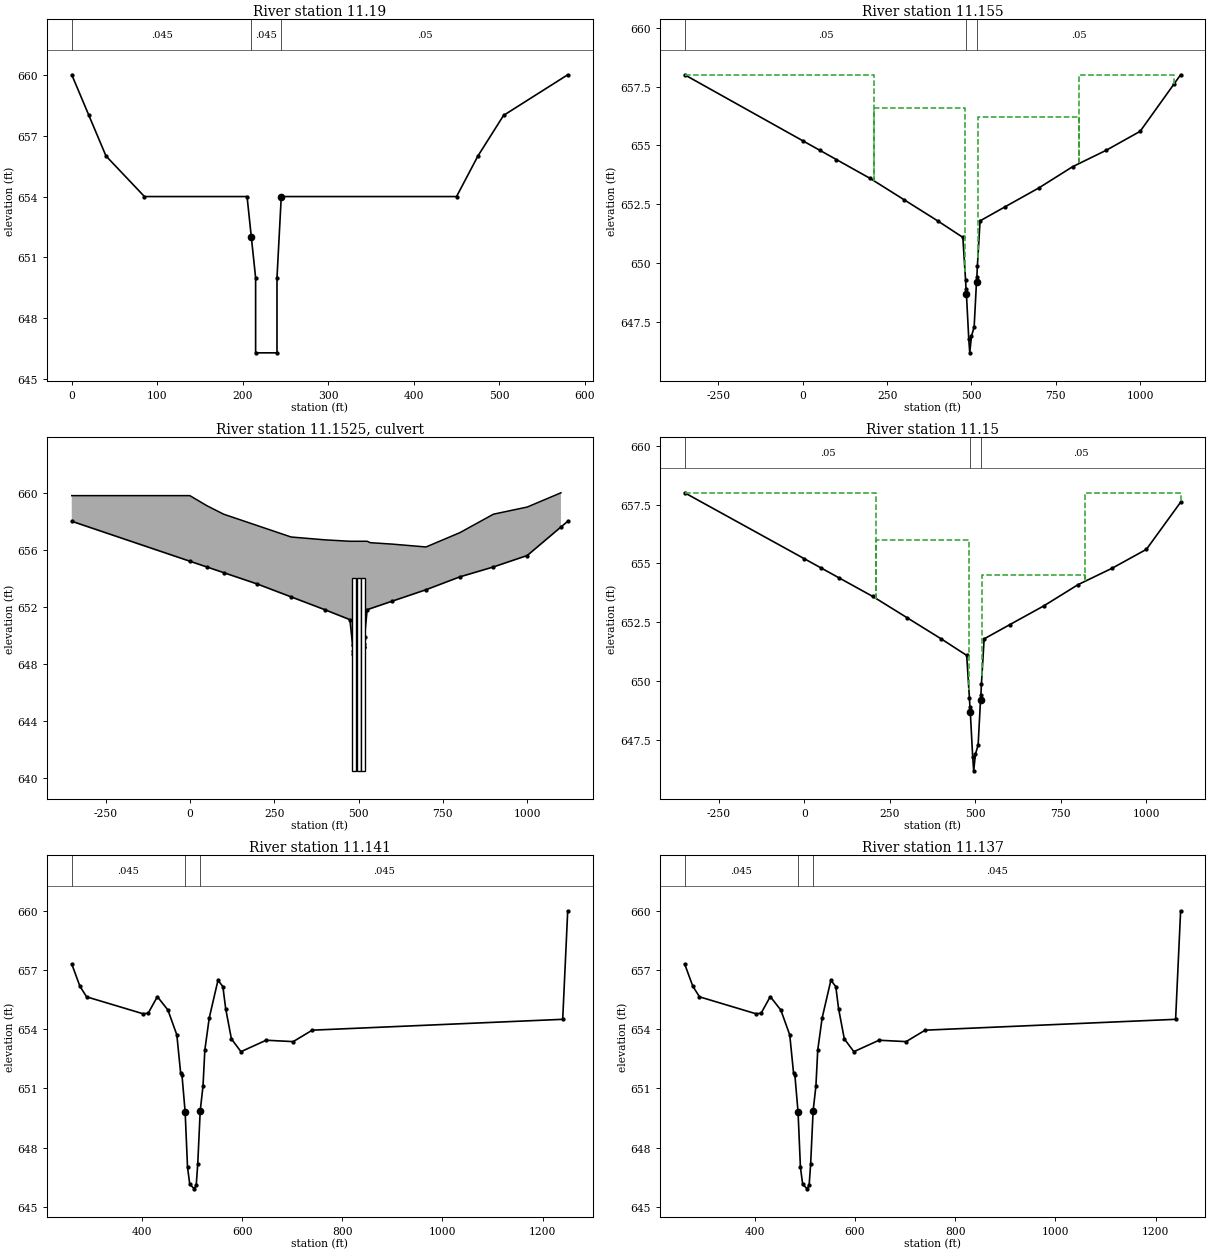
Type RM Length L Ch R = 1 ,11.19   ,88,88,98
#Sta/Elev= 15
       0     660      20     658      40     656      85     654     205     654
     210     652     215     650     215   646.3     240   646.3     240     650
     245     654     450     654     475     656     505     658     580     660
#Mann= 3 , 0 , 0
       0    .045       0     210    .045       0     245     .05       0
Bank Sta=210,245
XS Rating Curve= 0 ,0
Sediment Elevation=0
Exp/Cntr=0.3,0.1

Type RM Length L Ch R = 1 ,11.155  ,122.5,122.5,122.5
BEGIN DESCRIPTION:
This is a REPEATED section.
END DESCRIPTION:
#Sta/Elev= 28
    -350     658       0   655.2      50   654.8     100   654.4     200   653.6
     300   652.7     400   651.8   474.5   651.1   482.5   649.3     484   648.9
     485   648.7   485.1   648.7     492   646.8     495   646.2     500   646.9
     508   647.3   514.9   649.2     515   649.2     516   649.4   517.7   649.9
   525.5   651.8     600   652.4     700   653.2     800   654.1     900   654.8
    1000   655.6    1100   657.6    1120     658
#Mann= 3 , 0 , 0
    -350     .05       0     485    .035       0     515     .05       0
#XS Ineff= 4 ,-1
    -350     210     658     210     481   656.6     519     820   656.2
     820    1100     658
Permanent Ineff=
       F       F       F       F
Bank Sta=485,515
XS Rating Curve= 0 ,0
Sediment Elevation=0
Exp/Cntr=0.5,0.3

Type RM Length L Ch R = 2 ,11.1525 ,,,
BEGIN DESCRIPTION:
Bridge #4 - Culvert at CTH KR - WisDOT update to reflect 3 cells in the culvert
WisDOT SGN - August 2018
END DESCRIPTION:
Bridge Culvert--1,0,-1,-1, 0
Deck Dist Width WeirC Skew NumUp NumDn MinLoCord MaxHiCord MaxSubmerge Is_Ogee
73,48.5,2.5,0, 24, 24, 656.1, , 0.98, 0, 0,0,,
    -350       0      50     100     200     300     400   474.5   482.5     484
     485   485.1   514.9     515     516   517.7   525.5     535     600     700
     800     900    1000    1100
   659.8   659.8   659.1   658.5   657.7   656.9   656.7   656.6   656.6   656.6
   656.6   656.6   656.6   656.6   656.6   656.6   656.6   656.5   656.4   656.2
   657.2   658.5     659     660
                                                                                
                                                                                
                                
    -350       0      50     100     200     300     400   474.5   482.5     484
     485   485.1   514.9     515     516   517.7   525.5     535     600     700
     800     900    1000    1100
   659.8   659.8   659.1   658.5   657.7   656.9   656.7   656.6   656.6   656.6
   656.6   656.6   656.6   656.6   656.6   656.6   656.6   656.5   656.4   656.2
   657.2   658.5     659     660
                                                                                
                                                                                
                                
BR Coef=-1 , 0 , 0 ,0, 0 ,,,0.8,0,,1,
WSPro=,,,, 1 ,,,, 0 ,,,, 0 ,,,,-1 ,-1 ,-1 , 0 , 0 , 0 , 0 , 0
Multiple Barrel Culv=2,13.5,12,48.5,0.013,0.4,1,8,1,640.5,640.3, 3,Culvert #1  , 0 ,1
  487.17  487.17     500     500  512.83  512.83
Culvert Bottom n=0.022
Culvert Bottom Depth=5
Culvert Depth Blocked=5
BC Design=,, 0 ,, 0 ,,,,,,
BC Use User HTab Curves=0
BC User HTab FreeFlow(D)= 0

Type RM Length L Ch R = 1 ,11.15   ,10.5,10.5,10.5
BEGIN DESCRIPTION:
CTH KR / COUNTY LINE ROAD
END DESCRIPTION:
#Sta/Elev= 27
    -350     658       0   655.2      50   654.8     100   654.4     200   653.6
     300   652.7     400   651.8   474.5   651.1   482.5   649.3     484   648.9
     485   648.7   485.1   648.7     492   646.8     495   646.2     500   646.9
     508   647.3   514.9   649.2     515   649.2     516   649.4   517.7   649.9
   525.5   651.8     600   652.4     700   653.2     800   654.1     900   654.8
    1000   655.6    1100   657.6
#Mann= 3 , 0 , 0
    -350     .05       0     485    .035       0     515     .05       0
#XS Ineff= 4 ,-1
    -350     210     658     210     481     656     519     820   654.5
     820    1100     658
Permanent Ineff=
       F       F       F       F
Bank Sta=485,515
XS Rating Curve= 0 ,0
Sediment Elevation=0
Exp/Cntr=0.5,0.3

Type RM Length L Ch R = 1 ,11.141  ,27,27,27
BEGIN DESCRIPTION:
New Section for Ped Bridge
END DESCRIPTION:
#Sta/Elev= 30
     260   657.3  276.17  656.18  289.55  655.64  402.51  654.78  412.57  654.81
  430.84  655.65  451.93  654.97  469.73  653.71  477.39  651.76  479.97  651.68
  486.32   649.8  491.07     647  495.54  646.14  504.66  645.91  508.46   646.1
  511.46  647.17  516.38  649.86  521.99  651.12   525.6  652.94  534.41  654.57
  551.86  656.48  561.62  656.16  567.23  655.04  578.64  653.51  597.71  652.86
  647.97  653.44  702.03  653.37     740  653.95    1240   654.5    1250     660
#Mann= 3 , 0 , 0
     260    .045       0  486.32    .035       0  516.38    .045       0
#XS Ineff= 2 , 0
       0  430.84  655.65  551.86       0  656.48
Permanent Ineff=
       F       F
Bank Sta=486.32,516.38
XS Rating Curve= 0 ,0
Exp/Cntr=0.3,0.1

Type RM Length L Ch R = 1 ,11.137  ,40,40,40
BEGIN DESCRIPTION:
Copy of New Section for Ped Bridge
END DESCRIPTION:
#Sta/Elev= 30
     260   657.3  276.17  656.18  289.55  655.64  402.51  654.78  412.57  654.81
  430.84  655.65  451.93  654.97  469.73  653.71  477.39  651.76  479.97  651.68
  486.32   649.8  491.07     647  495.54  646.14  504.66  645.91  508.46   646.1
  511.46  647.17  516.38  649.86  521.99  651.12   525.6  652.94  534.41  654.57
  551.86  656.48  561.62  656.16  567.23  655.04  578.64  653.51  597.71  652.86
  647.97  653.44  702.03  653.37     740  653.95    1240   654.5    1250     660
#Mann= 3 , 0 , 0
     260    .045       0  486.32    .035       0  516.38    .045       0
#XS Ineff= 2 , 0
       0  430.84  655.65  551.86       0  656.48
Permanent Ineff=
       F       F
Bank Sta=486.32,516.38
XS Rating Curve= 0 ,0
Exp/Cntr=0.3,0.1

--- B30_143_144.g05 (geometry) ---

Geom Title=Ped Bridge at CTH KR - Corrected
Program Version=4.10

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
River Reach=RIVER-1         ,Reach-1

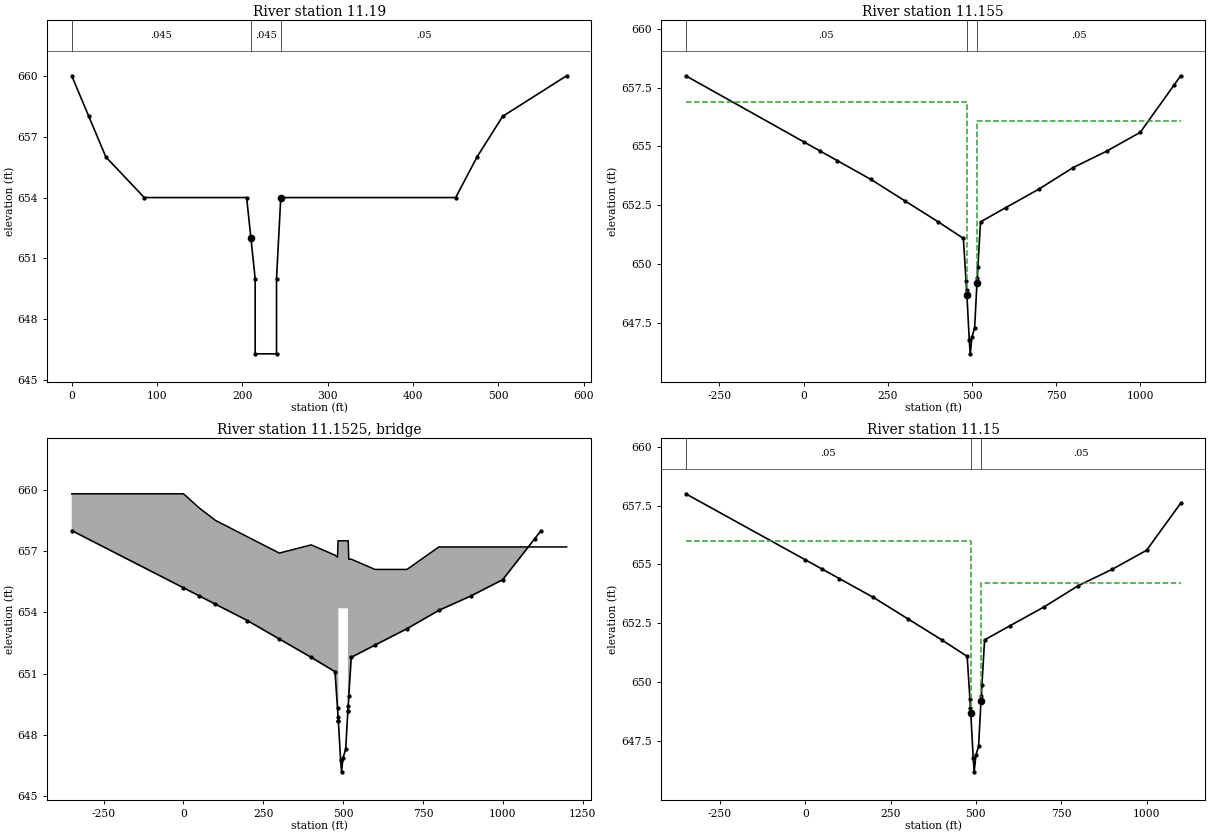
Type RM Length L Ch R = 1 ,11.19   ,160,160,170
#Sta/Elev= 15
       0     660      20     658      40     656      85     654     205     654
     210     652     215     650     215   646.3     240   646.3     240     650
     245     654     450     654     475     656     505     658     580     660
#Mann= 3 , 0 , 0
       0    .045       0     210    .045       0     245     .05       0
Bank Sta=210,245
XS Rating Curve= 0 ,0
Sediment Elevation=0
Exp/Cntr=0.3,0.1

Type RM Length L Ch R = 1 ,11.155  ,23,23,23
BEGIN DESCRIPTION:
This is a REPEATED section.
END DESCRIPTION:
#Sta/Elev= 28
    -350     658       0   655.2      50   654.8     100   654.4     200   653.6
     300   652.7     400   651.8   474.5   651.1   482.5   649.3     484   648.9
     485   648.7   485.1   648.7     492   646.8     495   646.2     500   646.9
     508   647.3   514.9   649.2     515   649.2     516   649.4   517.7   649.9
   525.5   651.8     600   652.4     700   653.2     800   654.1     900   654.8
    1000   655.6    1100   657.6    1120     658
#Mann= 3 , 0 , 0
    -350     .05       0     485    .035       0     515     .05       0
#XS Ineff= 2 , 0
             485   656.9     515           656.1
Permanent Ineff=
       F       F
Bank Sta=485,515
XS Rating Curve= 0 ,0
Sediment Elevation=0
Exp/Cntr=0.5,0.3

Type RM Length L Ch R = 3 ,11.1525 ,,,
BEGIN DESCRIPTION:
Bridge #4
Culvert at CTH KR
END DESCRIPTION:
Bridge Culvert--1,0,-1,-1, 0
Deck Dist Width WeirC Skew NumUp NumDn MinLoCord MaxHiCord MaxSubmerge Is_Ogee
1,21,2.5,0, 21, 21, 656.1, , 0.98, 0, 0,0,,
    -350       0      50     100     200     300     400   474.5   482.5     484
     485   485.1   514.9     515     516   517.7   525.5     600     700     800
    1200
   659.8   659.8   659.1   658.5   657.7   656.9   657.3   656.8   656.7   657.5
   657.5   657.5   657.5   657.5   657.5   656.6   656.6   656.1   656.1   657.2
   657.2
           655.2   654.8   654.4   653.6   652.7   651.8   651.1   649.3   648.9
   648.7   654.2   654.2   649.2   649.4   649.9   651.8   652.4   653.2   654.1
        
    -350       0      50     100     200     300     400   474.5   482.5     484
     485   485.1   514.9     515     516   517.7   525.5     600     700     800
    1200
   659.8   659.8   659.1   658.5   657.7   656.9   657.3   656.8   656.7   657.5
   657.5   657.5   657.5   657.5   657.5   656.6   656.6   656.1   656.1   657.2
   657.2
           655.2   654.8   654.4   653.6   652.7   651.8   651.1   649.3   648.9
   648.7   654.2   654.2   649.2   649.4   649.9   651.8   652.4   653.2   654.1
        
BR Coef=-1 , 0 , 0 ,0, 0 ,,,0.8,0,,1,
WSPro=,,,, 1 ,,,, 0 ,,,, 0 ,,,,-1 ,-1 ,-1 , 0 , 0 , 0 , 0 , 0
BC Design=,, 0 ,, 0 ,,,,,,
BC Use User HTab Curves=0
BC User HTab FreeFlow(D)= 0

Type RM Length L Ch R = 1 ,11.15   ,15,15,15
BEGIN DESCRIPTION:
CTH KR / COUNTY LINE ROAD
END DESCRIPTION:
#Sta/Elev= 27
    -350     658       0   655.2      50   654.8     100   654.4     200   653.6
     300   652.7     400   651.8   474.5   651.1   482.5   649.3     484   648.9
     485   648.7   485.1   648.7     492   646.8     495   646.2     500   646.9
     508   647.3   514.9   649.2     515   649.2     516   649.4   517.7   649.9
   525.5   651.8     600   652.4     700   653.2     800   654.1     900   654.8
    1000   655.6    1100   657.6
#Mann= 3 , 0 , 0
    -350     .05       0     485    .035       0     515     .05       0
#XS Ineff= 2 , 0
             485     656     515           654.2
Permanent Ineff=
       F       F
Bank Sta=485,515
XS Rating Curve= 0 ,0
Sediment Elevation=0
Exp/Cntr=0.5,0.3