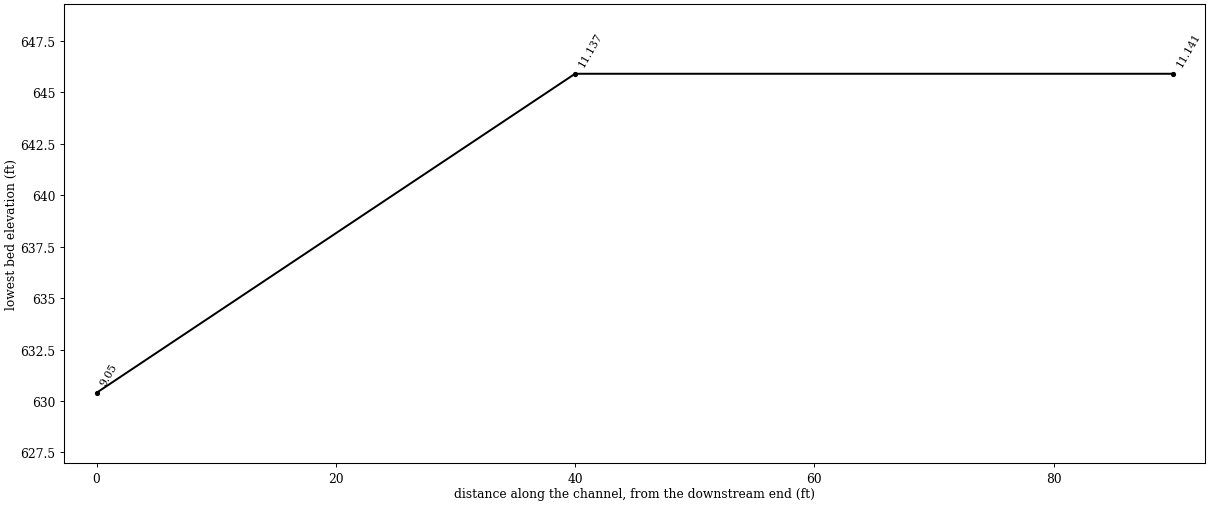
HEC-RAS study B30_143_144.prj: Pike River

--- B30_143_144.g05 (geometry) --- (continued)

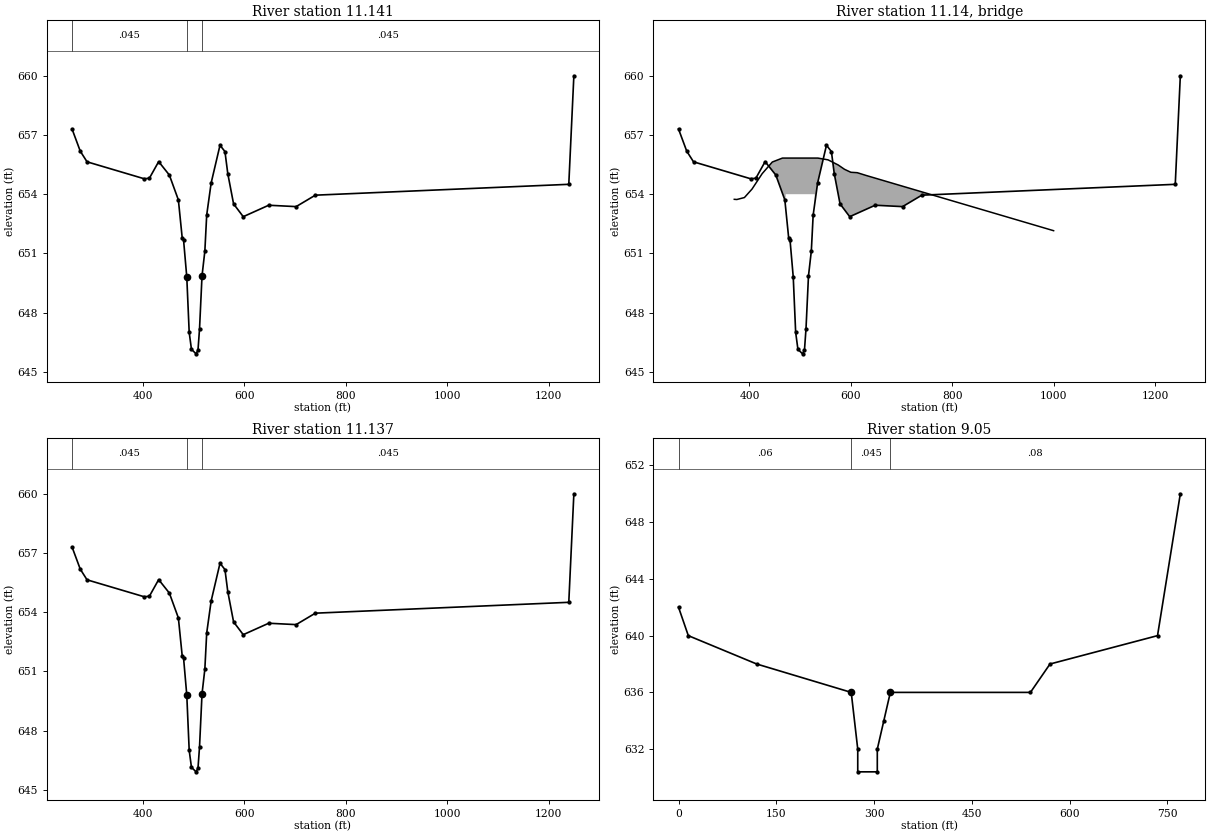
Type RM Length L Ch R = 1 ,11.141  ,50,50,50
BEGIN DESCRIPTION:
New Section for Ped Bridge
END DESCRIPTION:
#Sta/Elev= 30
     260   657.3  276.17  656.18  289.55  655.64  402.51  654.78  412.57  654.81
  430.84  655.65  451.93  654.97  469.73  653.71  477.39  651.76  479.97  651.68
  486.32   649.8  491.07     647  495.54  646.14  504.66  645.91  508.46   646.1
  511.46  647.17  516.38  649.86  521.99  651.12   525.6  652.94  534.41  654.57
  551.86  656.48  561.62  656.16  567.23  655.04  578.64  653.51  597.71  652.86
  647.97  653.44  702.03  653.37     740  653.95    1240   654.5    1250     660
#Mann= 3 , 0 , 0
     260    .045       0  486.32    .035       0  516.38    .045       0
#XS Ineff= 2 , 0
       0  430.84  655.65  551.86       0  656.48
Permanent Ineff=
       F       F
Bank Sta=486.32,516.38
XS Rating Curve= 0 ,0
Exp/Cntr=0.3,0.1

Type RM Length L Ch R = 3 ,11.14   ,,,
BEGIN DESCRIPTION:
Proposed Ped Bridge at CTH KR
END DESCRIPTION:
Bridge Culvert--1,0,-1,-1, 0
Deck Dist Width WeirC Skew NumUp NumDn MinLoCord MaxHiCord MaxSubmerge Is_Ogee
24,13,2.5,0, 19, 19, , , 0.98, 0, 0,0,,
     370     375     390     405     425     445     465  471.38  471.38  528.62
  528.62     535     555     575   587.5     600   612.5     630    1000
  653.74  653.73  653.83  654.26  655.04  655.63  655.83  655.83  655.83  655.83
  655.83  655.83  655.74  655.48  655.26  655.11  655.09  654.95  652.15
                                                             654     654     654
     654
     370     375     390     405     425     445     465  471.38  471.38  528.62
  528.62     535     555     575   587.5     600   612.5     630    1000
  653.74  653.73  653.83  654.26  655.04  655.63  655.83  655.83  655.83  655.83
  655.83  655.83  655.74  655.48  655.26  655.11  655.09  654.95  652.15
                                                             654     654     654
     654
BR Coef=-1 , 0 , 0 ,, 0 ,,,0.8,0,,1,
WSPro=,,,, 1 ,,,, 0 ,,,, 0 ,,,,-1 ,-1 ,-1 , 0 , 0 , 0 , 0 , 0
BC Design=,, 0 ,, 0 ,,,,,,
BC Use User HTab Curves=0
BC User HTab FreeFlow(D)= 0

Type RM Length L Ch R = 1 ,11.137  ,40,40,40
BEGIN DESCRIPTION:
Copy of New Section for Ped Bridge
END DESCRIPTION:
#Sta/Elev= 30
     260   657.3  276.17  656.18  289.55  655.64  402.51  654.78  412.57  654.81
  430.84  655.65  451.93  654.97  469.73  653.71  477.39  651.76  479.97  651.68
  486.32   649.8  491.07     647  495.54  646.14  504.66  645.91  508.46   646.1
  511.46  647.17  516.38  649.86  521.99  651.12   525.6  652.94  534.41  654.57
  551.86  656.48  561.62  656.16  567.23  655.04  578.64  653.51  597.71  652.86
  647.97  653.44  702.03  653.37     740  653.95    1240   654.5    1250     660
#Mann= 3 , 0 , 0
     260    .045       0  486.32    .035       0  516.38    .045       0
#XS Ineff= 2 , 0
       0  430.84  655.65  551.86       0  656.48
Permanent Ineff=
       F       F
Bank Sta=486.32,516.38
XS Rating Curve= 0 ,0
Exp/Cntr=0.3,0.1

Type RM Length L Ch R = 1 ,9.05    ,555,800,910
#Sta/Elev= 14
       0     642      15     640     120     638     265     636     275     632
     275   630.4     305   630.4     305     632     315     634     325     636
     540     636     570     638     735     640     770     650
#Mann= 3 , 0 , 0
       0     .06       0     265    .045       0     325     .08       0
Bank Sta=265,325
XS Rating Curve= 0 ,0
Exp/Cntr=0.3,0.1

--- B30_143_144.g08 (geometry) ---

Geom Title=Existing Condition
Program Version=4.10

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
River Reach=RIVER-1         ,Reach-1

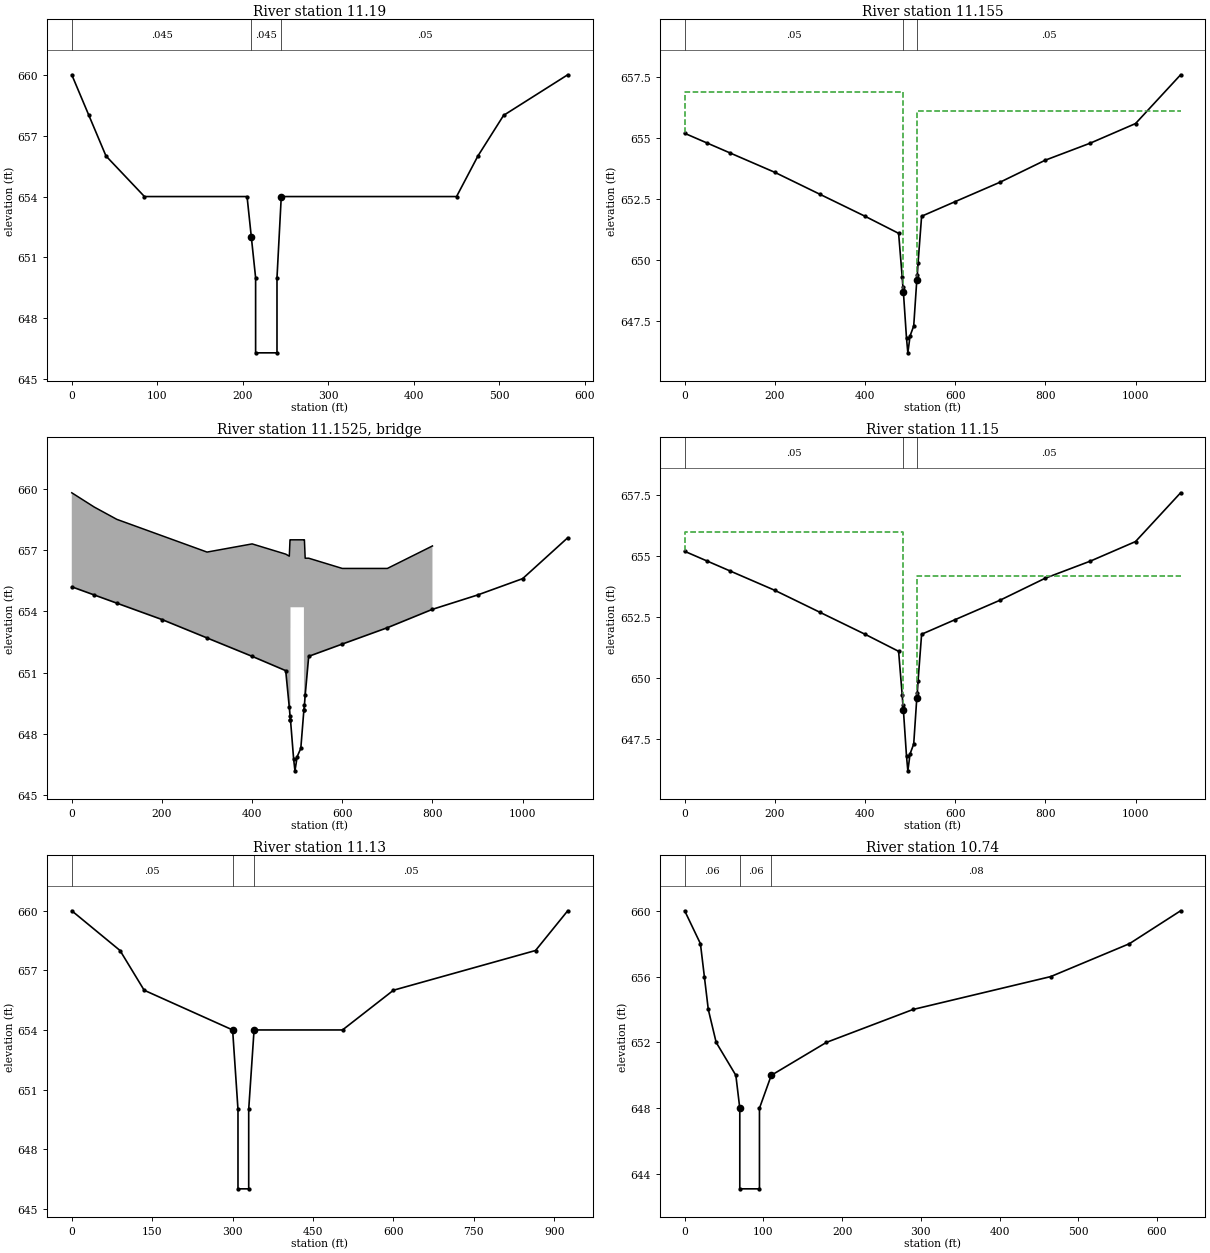
Type RM Length L Ch R = 1 ,11.19   ,160,160,170
#Sta/Elev= 15
       0     660      20     658      40     656      85     654     205     654
     210     652     215     650     215   646.3     240   646.3     240     650
     245     654     450     654     475     656     505     658     580     660
#Mann= 3 , 0 , 0
       0    .045       0     210    .045       0     245     .05       0
Bank Sta=210,245
XS Rating Curve= 0 ,0
Sediment Elevation=0
Exp/Cntr=0.3,0.1

Type RM Length L Ch R = 1 ,11.155  ,23,23,23
BEGIN DESCRIPTION:
This is a REPEATED section.
END DESCRIPTION:
#Sta/Elev= 26
       0   655.2      50   654.8     100   654.4     200   653.6     300   652.7
     400   651.8   474.5   651.1   482.5   649.3     484   648.9     485   648.7
   485.1   648.7     492   646.8     495   646.2     500   646.9     508   647.3
   514.9   649.2     515   649.2     516   649.4   517.7   649.9   525.5   651.8
     600   652.4     700   653.2     800   654.1     900   654.8    1000   655.6
    1100   657.6
#Mann= 3 , 0 , 0
       0     .05       0     485    .035       0     515     .05       0
#XS Ineff= 2 , 0
             485   656.9     515           656.1
Permanent Ineff=
       F       F
#Block Obstruct= 2 , 0
             260             800
Bank Sta=485,515
XS Rating Curve= 0 ,0
Sediment Elevation=0
Exp/Cntr=0.5,0.3

Type RM Length L Ch R = 3 ,11.1525 ,,,
BEGIN DESCRIPTION:
Bridge #4
Culvert at CTH KR
END DESCRIPTION:
Bridge Culvert--1,0,-1,-1, 0
Deck Dist Width WeirC Skew NumUp NumDn MinLoCord MaxHiCord MaxSubmerge Is_Ogee
1,21,2.5,0, 19, 19, 656.1, , 0.98, 0, 0,0,,
       0      50     100     200     300     400   474.5   482.5     484     485
   485.1   514.9     515     516   517.7   525.5     600     700     800
   659.8   659.1   658.5   657.7   656.9   657.3   656.8   656.7   657.5   657.5
   657.5   657.5   657.5   657.5   656.6   656.6   656.1   656.1   657.2
   655.2   654.8   654.4   653.6   652.7   651.8   651.1   649.3   648.9   648.7
   654.2   654.2   649.2   649.4   649.9   651.8   652.4   653.2   654.1
       0      50     100     200     300     400   474.5   482.5     484     485
   485.1   514.9     515     516   517.7   525.5     600     700     800
   659.8   659.1   658.5   657.7   656.9   657.3   656.8   656.7   657.5   657.5
   657.5   657.5   657.5   657.5   656.6   656.6   656.1   656.1   657.2
   655.2   654.8   654.4   653.6   652.7   651.8   651.1   649.3   648.9   648.7
   654.2   654.2   649.2   649.4   649.9   651.8   652.4   653.2   654.1
BR Coef=-1 , 0 , 0 ,0, 0 ,,,0.8,0,,1,
WSPro=,,,, 1 ,,,, 0 ,,,, 0 ,,,,-1 ,-1 ,-1 , 0 , 0 , 0 , 0 , 0
BC Design=,, 0 ,, 0 ,,,,,,
BC Use User HTab Curves=0
BC User HTab FreeFlow(D)= 0

Type RM Length L Ch R = 1 ,11.15   ,105,105,105
BEGIN DESCRIPTION:
 CTH KR / COUNTY LINE ROAD
END DESCRIPTION:
#Sta/Elev= 26
       0   655.2      50   654.8     100   654.4     200   653.6     300   652.7
     400   651.8   474.5   651.1   482.5   649.3     484   648.9     485   648.7
   485.1   648.7     492   646.8     495   646.2     500   646.9     508   647.3
   514.9   649.2     515   649.2     516   649.4   517.7   649.9   525.5   651.8
     600   652.4     700   653.2     800   654.1     900   654.8    1000   655.6
    1100   657.6
#Mann= 3 , 0 , 0
       0     .05       0     485    .035       0     515     .05       0
#XS Ineff= 2 , 0
             485     656     515           654.2
Permanent Ineff=
       F       F
#Block Obstruct= 2 , 0
             260             800
Bank Sta=485,515
XS Rating Curve= 0 ,0
Sediment Elevation=0
Exp/Cntr=0.5,0.3

Type RM Length L Ch R = 1 ,11.13   ,240,240,220
#Sta/Elev= 13
       0     660      90     658     135     656     300     654     310     650
     310     646     330     646     330     650     340     654     505     654
     600     656     865     658     925     660
#Mann= 3 , 0 , 0
       0     .05       0     300    .045       0     340     .05       0
#Block Obstruct= 2 , 0
                             700
Bank Sta=300,340
XS Rating Curve= 0 ,0
Sediment Elevation=0
Exp/Cntr=0.3,0.1

Type RM Length L Ch R = 1 ,10.74   ,720,820,555
#Sta/Elev= 16
       0     660      20     658      25     656      30     654      40     652
      65     650      70     648      70   643.1      95   643.1      95     648
     110     650     180     652     290     654     465     656     565     658
     630     660
#Mann= 3 , 0 , 0
       0     .06       0      70     .06       0     110     .08       0
Bank Sta=70,110
XS Rating Curve= 0 ,0
Sediment Elevation=0
Exp/Cntr=0.3,0.1

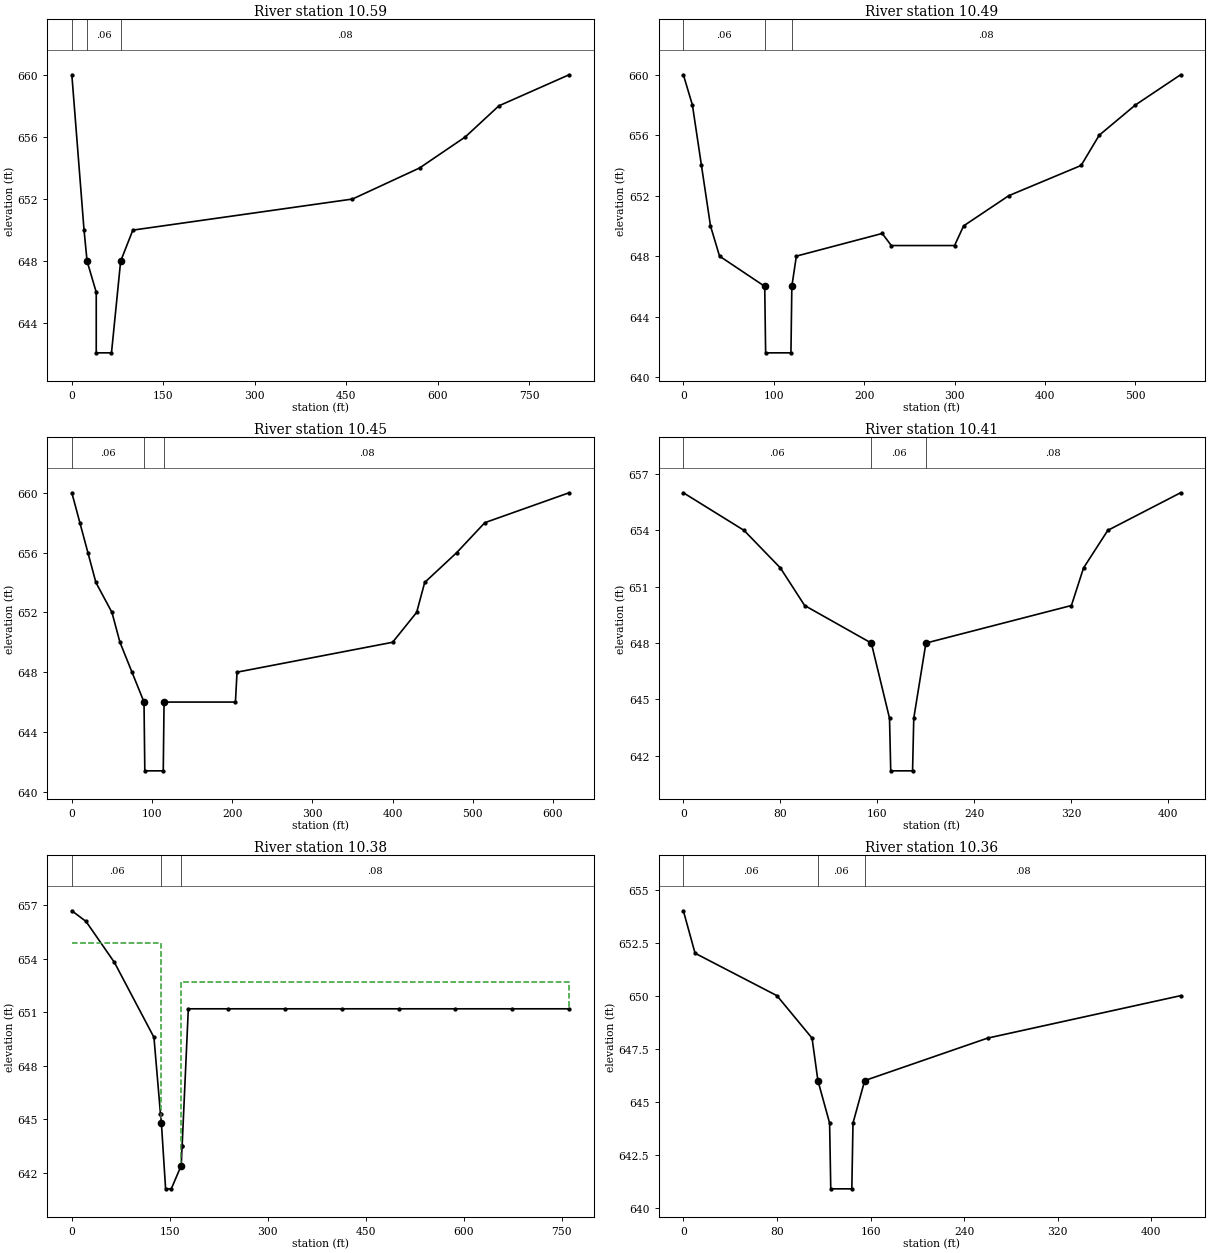
Type RM Length L Ch R = 1 ,10.59   ,555,590,440
#Sta/Elev= 13
       0     660      20     650      25     648      40     646      40   642.1
      65   642.1      80     648     100     650     460     652     570     654
     645     656     700     658     815     660
#Mann= 3 , 0 , 0
       0     .06       0      25     .06       0      80     .08       0
Bank Sta=25,80
XS Rating Curve= 0 ,0
Sediment Elevation=0
Exp/Cntr=0.3,0.1

Type RM Length L Ch R = 1 ,10.49   ,130,220,310
#Sta/Elev= 19
       0     660      10     658      20     654      30     650      40     648
      90     646      91   641.6     119   641.6     120     646     125     648
     220   649.5     230   648.7     300   648.7     310     650     360     652
     440     654     460     656     500     658     550     660
#Mann= 3 , 0 , 0
       0     .06       0      90     .06       0     120     .08       0
Bank Sta=90,120
XS Rating Curve= 0 ,0
Sediment Elevation=0
Exp/Cntr=0.3,0.1

Type RM Length L Ch R = 1 ,10.45   ,220,310,220
#Sta/Elev= 19
       0     660      10     658      20     656      30     654      50     652
      60     650      75     648      90     646      91   641.4     114   641.4
     115     646     204     646     206     648     400     650     430     652
     440     654     480     656     515     658     620     660
#Mann= 3 , 0 , 0
       0     .06       0      90     .06       0     115     .08       0
Bank Sta=90,115
XS Rating Curve= 0 ,0
Sediment Elevation=0
Exp/Cntr=0.3,0.1

Type RM Length L Ch R = 1 ,10.41   ,160,135,150
#Sta/Elev= 14
       0     656      50     654      80     652     100     650     155     648
     170     644     171   641.2     189   641.2     190     644     200     648
     320     650     330     652     350     654     410     656
#Mann= 3 , 0 , 0
       0     .06       0     155     .06       0     200     .08       0
#Block Obstruct= 2 , 0
                             290
Bank Sta=155,200
XS Rating Curve= 0 ,0
Sediment Elevation=0
Exp/Cntr=0.3,0.1

Type RM Length L Ch R = 1 ,10.38   ,75,75,75
BEGIN DESCRIPTION:
 STH 31 / GREEN BAY ROAD
END DESCRIPTION:
#Sta/Elev= 22
       0   656.7   21.75   656.1   65.25   653.8 125.715   649.6  135.72   645.3
 135.807   645.3 137.025   644.8 137.112   644.8  143.55   641.1  152.25   641.1
 167.388   642.4 167.475   642.4  168.78   643.5 168.867   643.5  178.35   651.2
  239.25   651.2  326.25   651.2  413.25   651.2  500.25   651.2  587.25   651.2
  674.25   651.2  761.25   651.2
#Mann= 3 , 0 , 0
       0     .06       0 137.025    .035       0 167.475     .08       0
#XS Ineff= 2 , 0
         137.025   654.9 167.475           652.7
Permanent Ineff=
       F       F
Bank Sta=137.025,167.475
XS Rating Curve= 0 ,0
Sediment Elevation=0
Exp/Cntr=0.5,0.3

Type RM Length L Ch R = 1 ,10.36   ,500,555,380
#Sta/Elev= 12
       0     654      10     652      80     650     110     648     115     646
     125     644     126   640.9     144   640.9     145     644     155     646
     260     648     425     650
#Mann= 3 , 0 , 0
       0     .06       0     115     .06       0     155     .08       0
#Block Obstruct= 2 , 0
             100             180
Bank Sta=115,155
XS Rating Curve= 0 ,0
Exp/Cntr=0.3,0.1

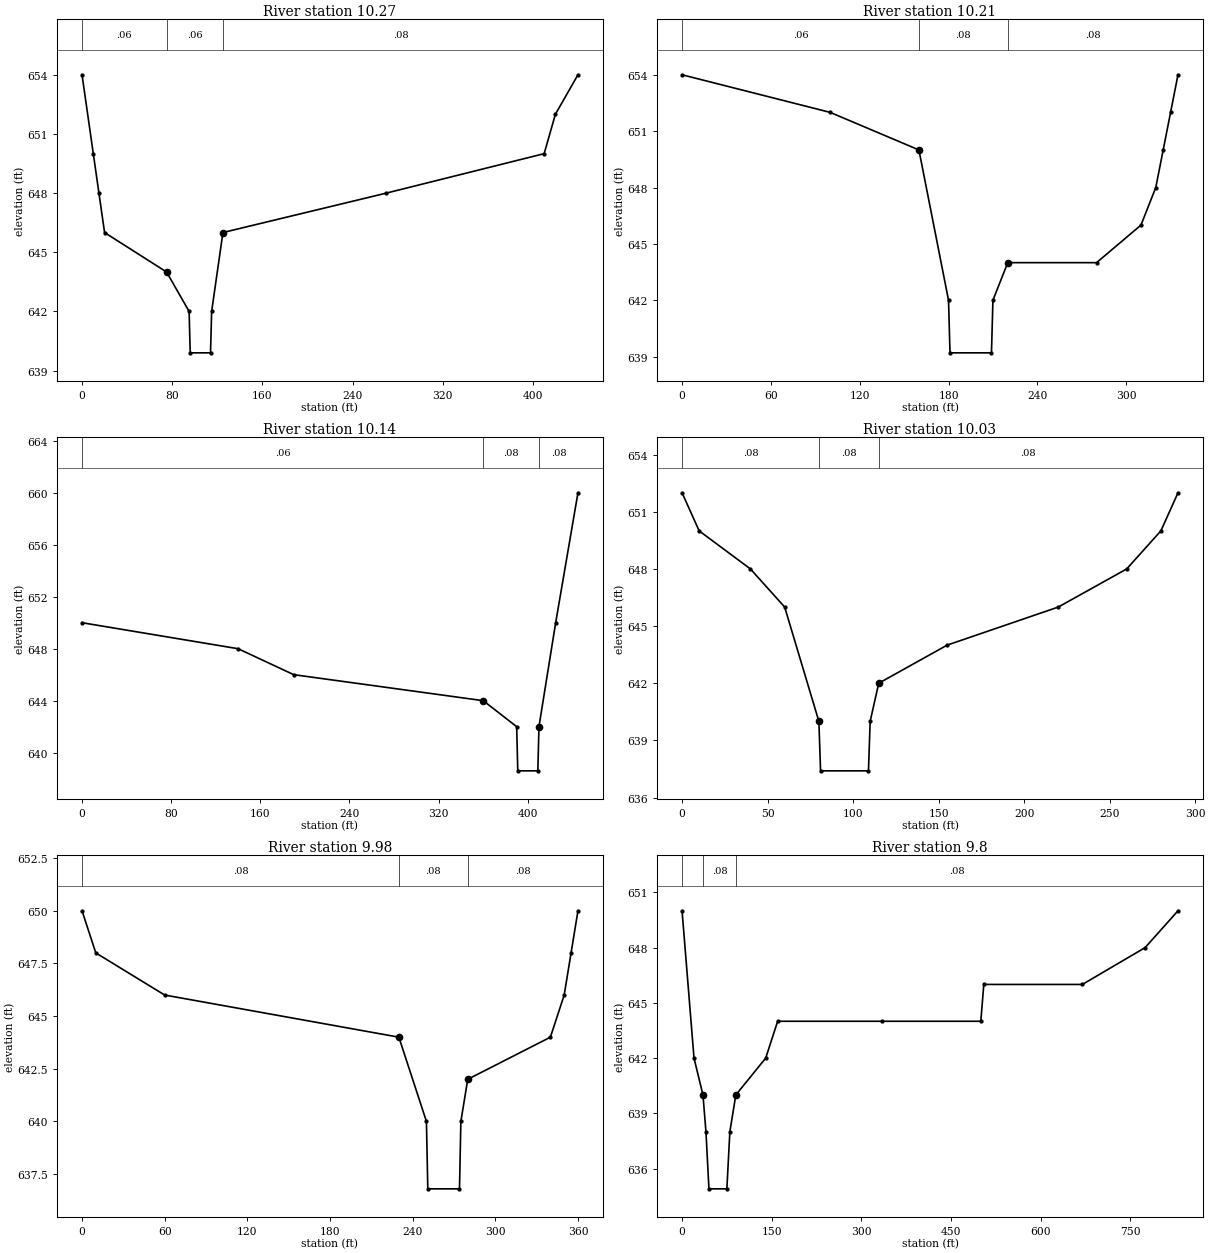
Type RM Length L Ch R = 1 ,10.27   ,320,430,455
#Sta/Elev= 14
       0     654      10     650      15     648      20     646      75     644
      95     642      96   639.9     114   639.9     115     642     125     646
     270     648     410     650     420     652     440     654
#Mann= 3 , 0 , 0
       0     .06       0      75     .06       0     125     .08       0
#Block Obstruct= 2 , 0
                             280
Bank Sta=75,125
XS Rating Curve= 0 ,0
Exp/Cntr=0.3,0.1

Type RM Length L Ch R = 1 ,10.21   ,330,440,440
#Sta/Elev= 14
       0     654     100     652     160     650     180     642     181   639.2
     209   639.2     210     642     220     644     280     644     310     646
     320     648     325     650     330     652     335     654
#Mann= 3 , 0 , 0
       0     .06       0     160     .08       0     220     .08       0
Bank Sta=160,220
XS Rating Curve= 0 ,0
Exp/Cntr=0.3,0.1

Type RM Length L Ch R = 1 ,10.14   ,580,640,530
#Sta/Elev= 10
       0     650     140     648     190     646     360     644     390     642
     391   638.6     409   638.6     410     642     425     650     445     660
#Mann= 3 , 0 , 0
       0     .06       0     360     .08       0     410     .08       0
#Block Obstruct= 2 , 0
             200
Bank Sta=360,410
XS Rating Curve= 0 ,0
Exp/Cntr=0.3,0.1

Type RM Length L Ch R = 1 ,10.03   ,270,240,255
#Sta/Elev= 14
       0     652      10     650      40     648      60     646      80     640
      81   637.4     109   637.4     110     640     115     642     155     644
     220     646     260     648     280     650     290     652
#Mann= 3 , 0 , 0
       0     .08       0      80     .08       0     115     .08       0
Bank Sta=80,115
XS Rating Curve= 0 ,0
Exp/Cntr=0.3,0.1

Type RM Length L Ch R = 1 ,9.98    ,800,1020,440
#Sta/Elev= 13
       0     650      10     648      60     646     230     644     250     640
     251   636.8     274   636.8     275     640     280     642     340     644
     350     646     355     648     360     650
#Mann= 3 , 0 , 0
       0     .08       0     230     .08       0     280     .08       0
Bank Sta=230,280
XS Rating Curve= 0 ,0
Exp/Cntr=0.3,0.1

Type RM Length L Ch R = 1 ,9.8     ,670,655,440
#Sta/Elev= 16
       0     650      20     642      35     640      40     638      45   634.9
      75   634.9      80     638      90     640     140     642     160     644
     335     644     500     644     505     646     670     646     775     648
     830     650
#Mann= 3 , 0 , 0
       0     .08       0      35     .08       0      90     .08       0
#Block Obstruct= 2 , 0
                             575
Bank Sta=35,90
XS Rating Curve= 0 ,0
Exp/Cntr=0.3,0.1

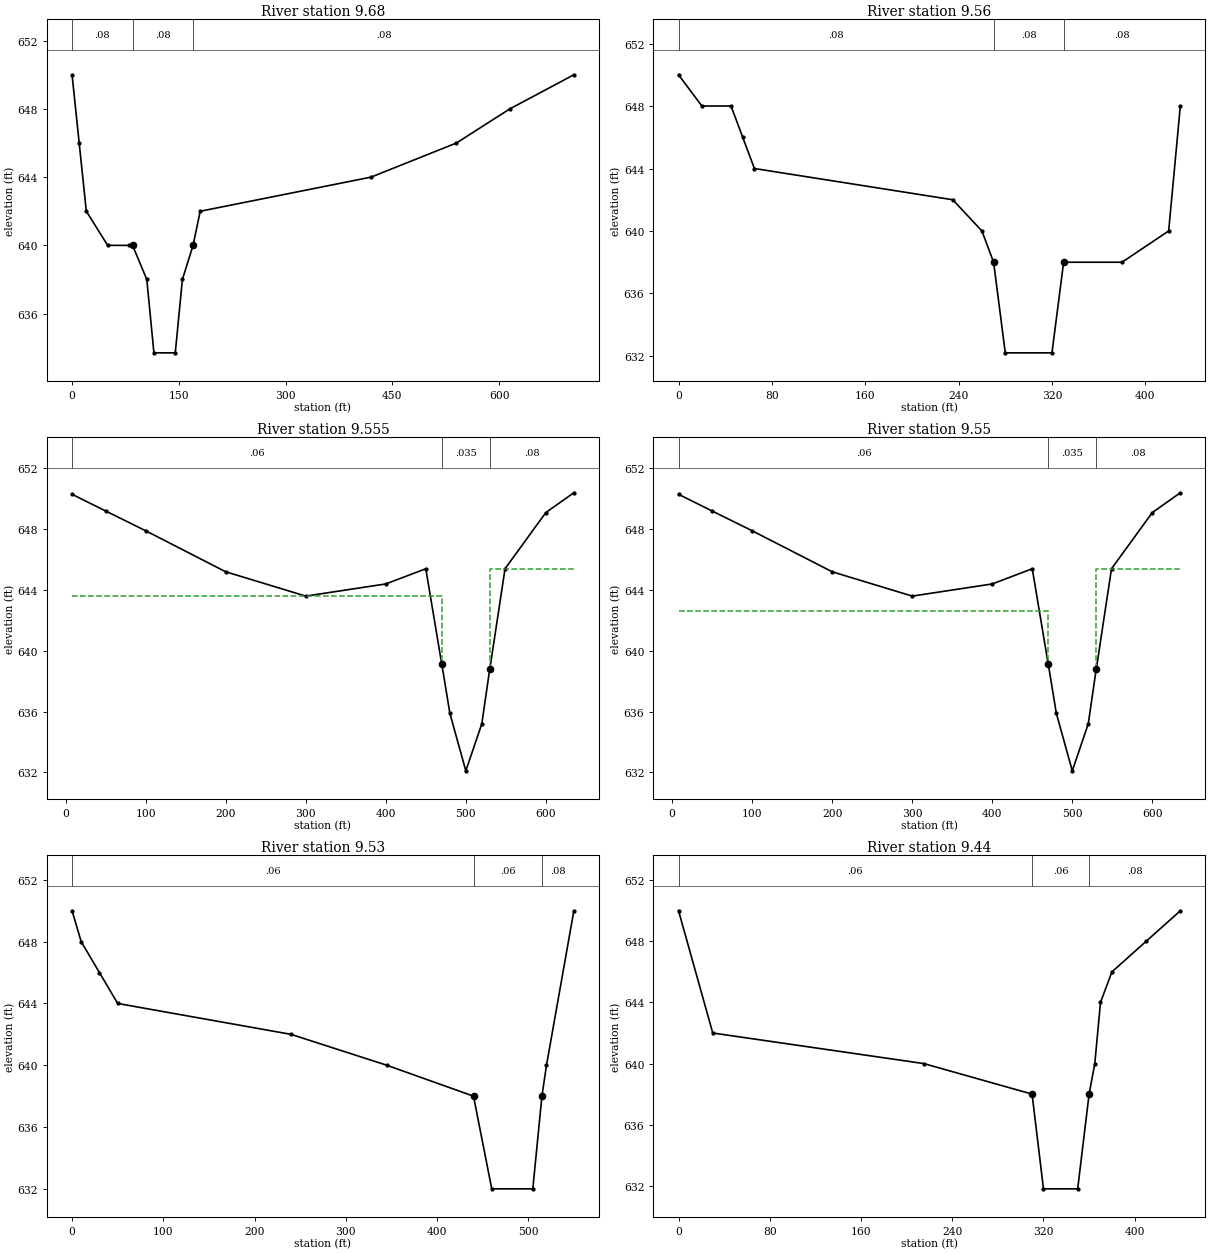
Type RM Length L Ch R = 1 ,9.68    ,490,640,770
#Sta/Elev= 16
       0     650      10     646      20     642      50     640      80     640
      85     640     105     638     115   633.7     145   633.7     155     638
     170     640     180     642     420     644     540     646     615     648
     705     650
#Mann= 3 , 0 , 0
       0     .08       0      85     .08       0     170     .08       0
Bank Sta=85,170
XS Rating Curve= 0 ,0
Exp/Cntr=0.3,0.1

Type RM Length L Ch R = 1 ,9.56    ,116,56,86
#Sta/Elev= 14
       0     650      20     648      45     648      55     646      65     644
     235     642     260     640     270     638     280   632.2     320   632.2
     330     638     380     638     420     640     430     648
#Mann= 3 , 0 , 0
       0     .08       0     270     .08       0     330     .08       0
Bank Sta=270,330
XS Rating Curve= 0 ,0
Exp/Cntr=0.3,0.1

Type RM Length L Ch R = 1 ,9.555   ,34,34,34
BEGIN DESCRIPTION:
This is a REPEATED section.
END DESCRIPTION:
#Sta/Elev= 17
       8   650.3      50   649.2     100   647.9     200   645.2     300   643.6
     400   644.4     450   645.4     470   639.1   470.1   639.1     480   635.9
     500   632.1     520   635.2   529.9   638.8     530   638.8     549   645.4
     600   649.1     635   650.4
#Mann= 3 , 0 , 0
       8     .06       0     470    .035       0     530     .08       0
#XS Ineff= 2 , 0
             470   643.6     530           645.4
Permanent Ineff=
       F       F
#Block Obstruct= 2 , 0
             200
Bank Sta=470,530
XS Rating Curve= 0 ,0
Exp/Cntr=0.5,0.3

Type RM Length L Ch R = 1 ,9.55    ,90,90,90
BEGIN DESCRIPTION:
 CTH A / 7TH STREET
END DESCRIPTION:
#Sta/Elev= 17
       8   650.3      50   649.2     100   647.9     200   645.2     300   643.6
     400   644.4     450   645.4     470   639.1   470.1   639.1     480   635.9
     500   632.1     520   635.2   529.9   638.8     530   638.8     549   645.4
     600   649.1     635   650.4
#Mann= 3 , 0 , 0
       8     .06       0     470    .035       0     530     .08       0
#XS Ineff= 2 , 0
             470   642.6     530           645.4
Permanent Ineff=
       F       F
#Block Obstruct= 2 , 0
             200
Bank Sta=470,530
XS Rating Curve= 0 ,0
Exp/Cntr=0.5,0.3

Type RM Length L Ch R = 1 ,9.53    ,440,530,555
#Sta/Elev= 12
       0     650      10     648      30     646      50     644     240     642
     345     640     440     638     460     632     505     632     515     638
     520     640     550     650
#Mann= 3 , 0 , 0
       0     .06       0     440     .06       0     515     .08       0
#Block Obstruct= 2 , 0
             200
Bank Sta=440,515
XS Rating Curve= 0 ,0
Exp/Cntr=0.3,0.1

Type RM Length L Ch R = 1 ,9.44    ,170,140,130
#Sta/Elev= 12
       0     650      30     642     215     640     310     638     320   631.8
     350   631.8     360     638     365     640     370     644     380     646
     410     648     440     650
#Mann= 3 , 0 , 0
       0     .06       0     310     .06       0     360     .08       0
#Block Obstruct= 2 , 0
             100
Bank Sta=310,360
XS Rating Curve= 0 ,0
Exp/Cntr=0.3,0.1

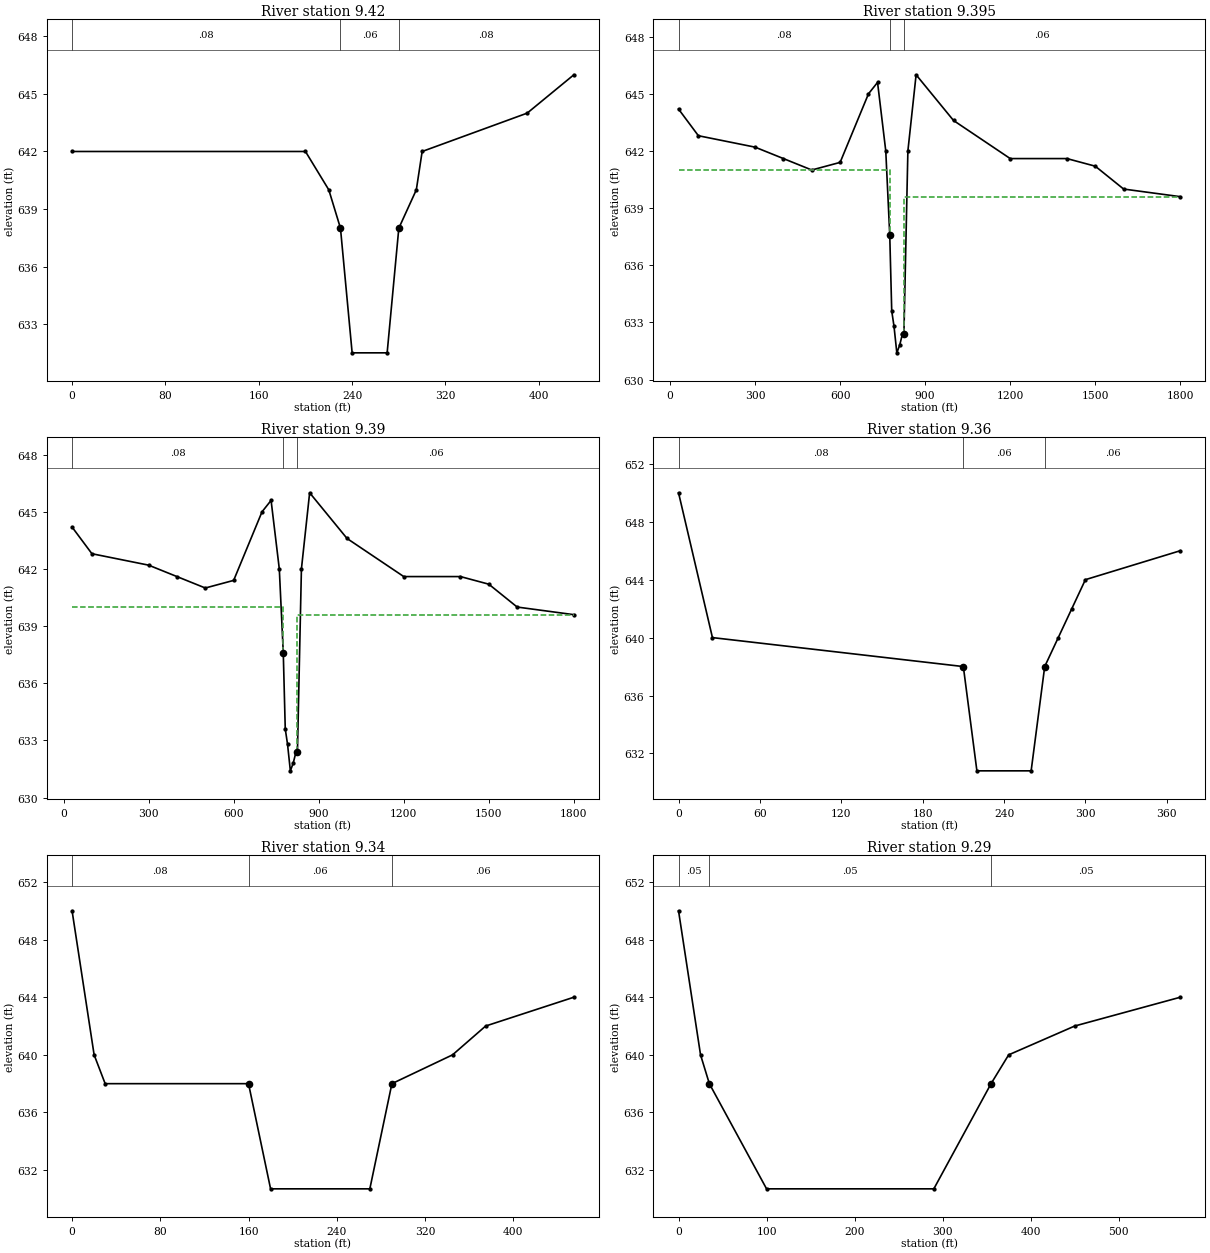
Type RM Length L Ch R = 1 ,9.42    ,95,125,145
#Sta/Elev= 11
       0     642     200     642     220     640     230     638     240   631.5
     270   631.5     280     638     295     640     300     642     390     644
     430     646
#Mann= 3 , 0 , 0
       0     .08       0     230     .06       0     280     .08       0
#Block Obstruct= 2 , 0
                             390
Bank Sta=230,280
XS Rating Curve= 0 ,0
Exp/Cntr=0.3,0.1

Type RM Length L Ch R = 1 ,9.395   ,44.2,44.2,44.2
BEGIN DESCRIPTION:
This is a REPEATED section.
END DESCRIPTION:
#Sta/Elev= 25
      30   644.2     100   642.8     300   642.2     400   641.6     500     641
     600   641.4     700     645     732   645.6     761     642     775   637.6
     782   633.6     790   632.8     800   631.4     810   631.8     820   632.4
   824.9   632.4     825   632.4     839     642     868     646    1000   643.6
    1200   641.6    1400   641.6    1500   641.2    1600     640    1800   639.6
#Mann= 3 , 0 , 0
      30     .08       0     775    .035       0     825     .06       0
#XS Ineff= 2 , 0
             775     641     825           639.6
Permanent Ineff=
       F       F
#Block Obstruct= 2 , 0
             600             825
Bank Sta=775,825
XS Rating Curve= 0 ,0
Exp/Cntr=0.5,0.3

Type RM Length L Ch R = 1 ,9.39    ,140,110,50
BEGIN DESCRIPTION:
 PETRIFYING SPRINGS PARK DR
END DESCRIPTION:
#Sta/Elev= 25
      30   644.2     100   642.8     300   642.2     400   641.6     500     641
     600   641.4     700     645     732   645.6     761     642     775   637.6
     782   633.6     790   632.8     800   631.4     810   631.8     820   632.4
   824.9   632.4     825   632.4     839     642     868     646    1000   643.6
    1200   641.6    1400   641.6    1500   641.2    1600     640    1800   639.6
#Mann= 3 , 0 , 0
      30     .08       0     775    .035       0     825     .06       0
#XS Ineff= 2 , 0
             775     640     825           639.6
Permanent Ineff=
       F       F
#Block Obstruct= 2 , 0
             600             825
Bank Sta=775,825
XS Rating Curve= 0 ,0
Exp/Cntr=0.5,0.3

Type RM Length L Ch R = 1 ,9.36    ,220,130,130
#Sta/Elev= 10
       0     650      25     640     210     638     220   630.8     260   630.8
     270     638     280     640     290     642     300     644     370     646
#Mann= 3 , 0 , 0
       0     .08       0     210     .06       0     270     .06       0
Bank Sta=210,270
XS Rating Curve= 0 ,0
Exp/Cntr=0.3,0.1

Type RM Length L Ch R = 1 ,9.34    ,490,280,240
#Sta/Elev= 10
       0     650      20     640      30     638     160     638     180   630.7
     270   630.7     290     638     345     640     375     642     455     644
#Mann= 3 , 0 , 0
       0     .08       0     160     .06       0     290     .06       0
Bank Sta=160,290
XS Rating Curve= 0 ,0
Exp/Cntr=0.3,0.1

Type RM Length L Ch R = 1 ,9.29    ,380,480,610
#Sta/Elev= 9
       0     650      25     640      35     638     100   630.7     290   630.7
     355     638     375     640     450     642     570     644
#Mann= 3 , 0 , 0
       0     .05       0      35     .05       0     355     .05       0
Bank Sta=35,355
XS Rating Curve= 0 ,0
Exp/Cntr=0.3,0.1

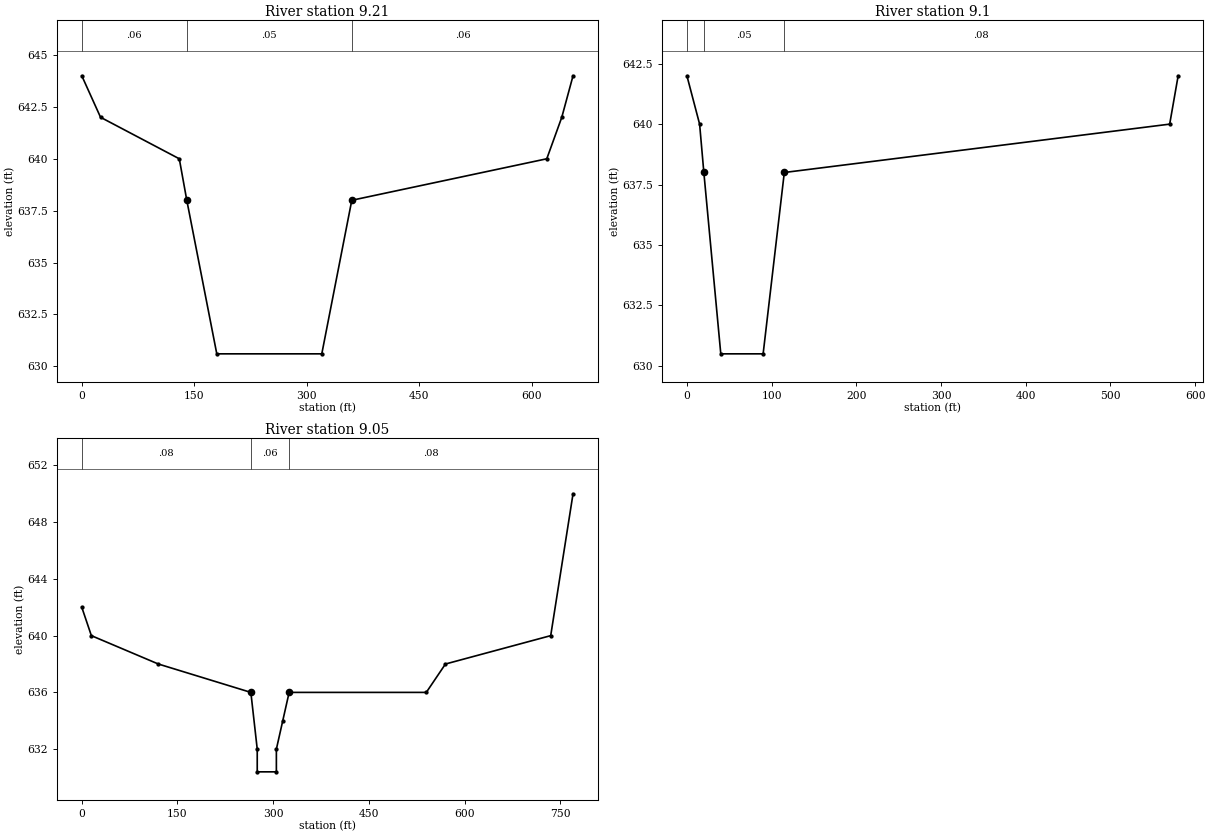
Type RM Length L Ch R = 1 ,9.21    ,610,640,580
#Sta/Elev= 10
       0     644      25     642     130     640     140     638     180   630.6
     320   630.6     360     638     620     640     640     642     655     644
#Mann= 3 , 0 , 0
       0     .06       0     140     .05       0     360     .06       0
Bank Sta=140,360
XS Rating Curve= 0 ,0
Exp/Cntr=0.3,0.1

Type RM Length L Ch R = 1 ,9.1     ,300,290,230
#Sta/Elev= 8
       0     642      15     640      20     638      40   630.5      90   630.5
     115     638     570     640     580     642
#Mann= 3 , 0 , 0
       0     .08       0      20     .05       0     115     .08       0
Bank Sta=20,115
XS Rating Curve= 0 ,0
Exp/Cntr=0.3,0.1

Type RM Length L Ch R = 1 ,9.05    ,555,800,910
#Sta/Elev= 14
       0     642      15     640     120     638     265     636     275     632
     275   630.4     305   630.4     305     632     315     634     325     636
     540     636     570     638     735     640     770     650
#Mann= 3 , 0 , 0
       0     .08       0     265     .06       0     325     .08       0
Bank Sta=265,325
XS Rating Curve= 0 ,0
Exp/Cntr=0.3,0.1